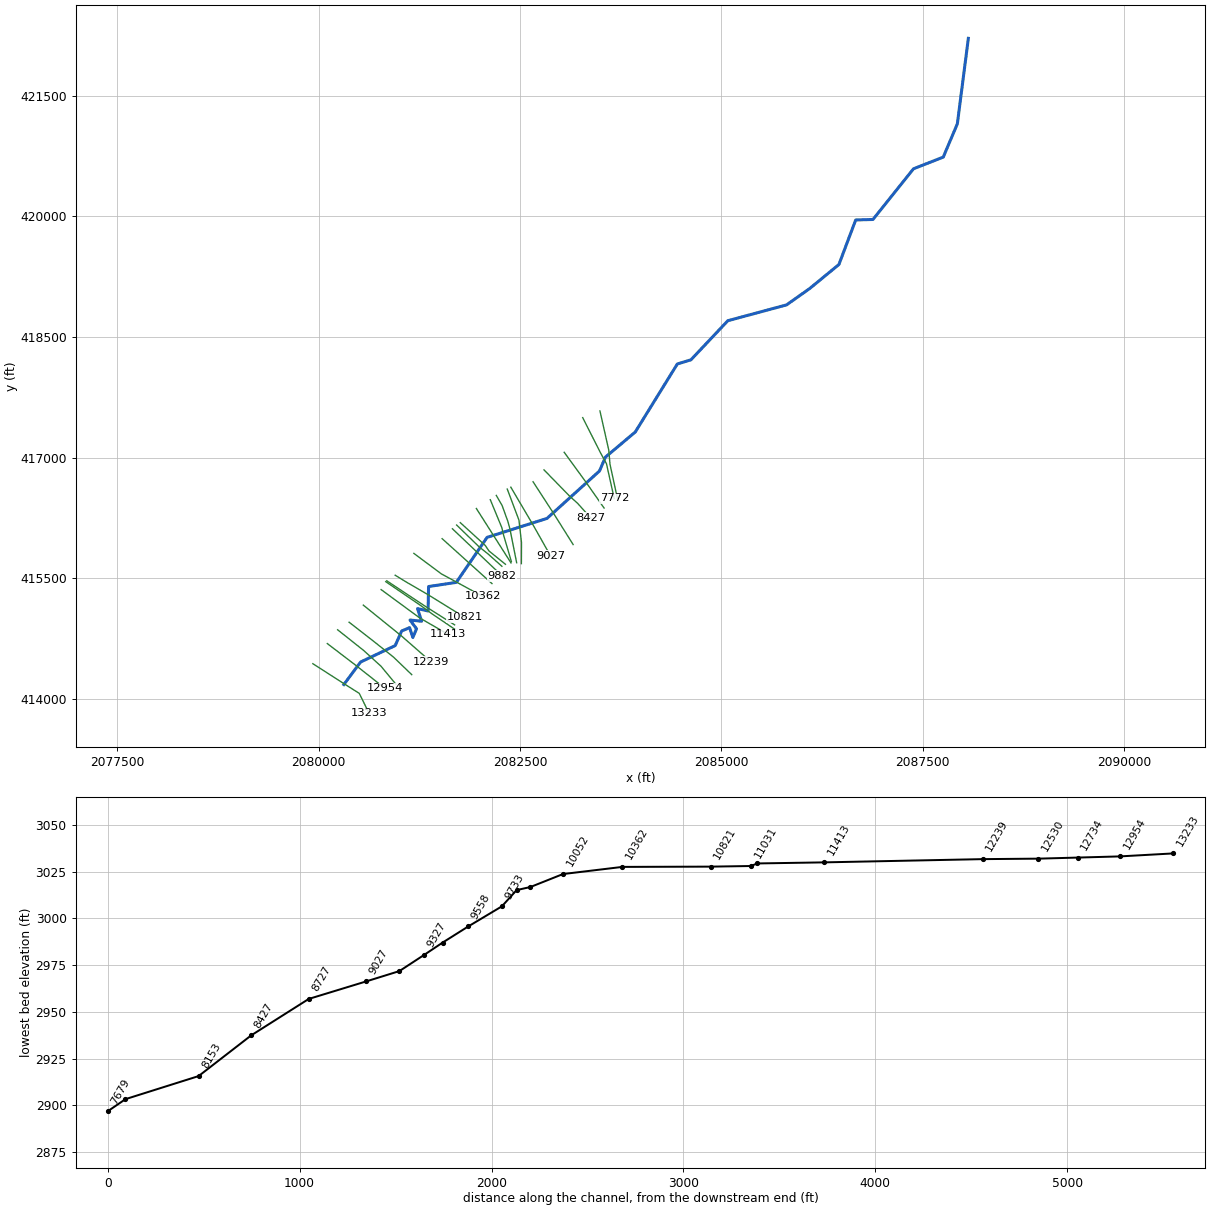
--- MCMILLCK.prj (project) ---

Proj Title=MCMILLCK
Current Plan=p01
Default Exp/Contr=0.3,0.1
English Units
Geom File=g01
Flow File=f01
Plan File=p01
Y Axis Title=Elevation
X Axis Title(PF)=Main Channel Distance
X Axis Title(XS)=Station
BEGIN DESCRIPTION:
Stream Name- McMillion Creek
Flood Zone: Zone A
Greenbrier County, WV
County-Wide Study
WVDHSEM-2018-3, Flood Risk Project
HEC-RAS Version: 5.0.7
General Notes:
For the Hydrology Regression was used.
END DESCRIPTION:
DSS Export Rating Curves= 0
DSS Export Rating Curve Sorted= 0
DSS Export Volume Flow Curves= 0
DXF Filename=..\M2.
DXF OffsetX= 0
DXF OffsetY= 0
DXF ScaleX= 1
DXF ScaleY= 10

--- MCMILLCK.p01 (plan) ---

Plan Title=Floodplain
Program Version=5.07
Short Identifier=Floodplain
Geom File=g01
Flow File=f01
Subcritical Flow
K Sum by GR= 0
Std Step Tol= 0.01
Critical Tol= 0.01
Num of Std Step Trials= 20
Max Error Tol= 0.3
Flow Tol Ratio= 0.001
Split Flow NTrial= 30
Split Flow Tol= 0.02
Split Flow Ratio= 0.02
Log Output Level= 0
Friction Slope Method= 1
Unsteady Friction Slope Method= 2
Unsteady Bridges Friction Slope Method= 1
Parabolic Critical Depth
Global Vel Dist= 0 , 0 , 0
Global Log Level= 0
CheckData=True
Encroach Param=-1 ,0,0, 0
Computation Interval=1MIN
Output Interval=1HOUR
Instantaneous Interval=1HOUR
Mapping Interval=1HOUR
Computation Time Step Use Courant=        0
Computation Time Step Use Time Series=    0
Computation Time Step Count To Double=0
Computation Time Step Max Doubling=0
Computation Time Step Max Halving=0
Computation Time Step Residence Courant=0
Run HTab= 0
Run UNet= 0
Run Sediment= 0
Run PostProcess= 0
Run WQNet= 0
Run RASMapper= 0
UNET Theta= 1
UNET Theta Warmup= 1
UNET ZTol= 0.02
UNET ZSATol= 0.02
UNET MxIter= 20
UNET Max Iter WO Improvement= 0
UNET MaxInSteps= 0
UNET DtIC= 0
UNET DtMin= 0
UNET MaxCRTS= 20
UNET WFStab= 2
UNET SFStab= 1
UNET WFX= 1
UNET SFX= 1
UNET 1D Methodology=Finite Difference
UNET DSS MLevel= 4
UNET Pardiso=0
UNET DZMax Abort= 100
UNET Use Existing IB Tables=-1
UNET Froude Reduction=False
UNET Froude Limit= 0.8
UNET Froude Power= 4
UNET D1 Cores= 0
UNET D2 Coriolis=0
UNET D2 Cores= 0
UNET D2 Theta= 1
UNET D2 Theta Warmup= 1
UNET D2 Z Tol= 0.01
UNET D2 Volume Tol= 0.01
UNET D2 Max Iterations= 20
UNET D2 Equation= 0
UNET D2 RampUpFraction=0.1
UNET D2 TimeSlices= 1
UNET D2 BCVolumeCheck=0
UNET D1D2 MaxIter= 0
UNET D1D2 ZTol=0.01
UNET D1D2 QTol=0.1
UNET D1D2 MinQTol=1
Write IC File= 0
Write IC File at Fixed DateTime=0
Write IC File at Sim End=0
Echo Input=False
Echo Parameters=False
Echo Output=False
Write Detailed= 0
HDF Write Warmup=0
HDF Write Time Slices=0
HDF Flush=0
HDF Face Node Velocities=0
HDF Compression= 1
HDF Chunk Size= 1
HDF Spatial Parts= 1
HDF Use Max Rows=0
HDF Fixed Rows= 1
Calibration Method= 0
Calibration Iterations= 20
Calibration Max Change=0.05
Calibration Tolerance=0.2
Calibration Maximum=1.5
Calibration Minimum=0.5
Calibration Optimization Method= 1
WQ AD Non Conservative
WQ ULTIMATE=-1
WQ Max Comp Step=1HOUR
WQ Output Interval=15MIN
WQ Output Selected Increments= 0
WQ Output face flow=0
WQ Output face velocity=0
WQ Output face area=0
WQ Output face dispersion=0
WQ Output cell volume=0
WQ Output cell surface area=0
WQ Output cell continuity=0
WQ Output cumulative cell continuity=0
WQ Output face conc=0
WQ Output face dconc_dx=0
WQ Output face courant=0
WQ Output face peclet=0
WQ Output face adv mass=0
WQ Output face disp mass=0
WQ Output cell mass=0
WQ Output cell source sink temp=0
WQ Output nsm pathways=0
WQ Output nsm derived pathways=0
WQ Output MaxMinRange=-1
WQ Daily Max Min Mean=-1
WQ Daily Range=0
WQ Daily Time=0
WQ Create Restart=0
WQ Fixed Restart=0
WQ System Summary=0
WQ Write To DSS=0
WQ Use Fixed Temperature=0
Sorting and Armoring Iterations= 10
XS Update Threshold= 0.02
Bed Roughness Predictor= 0
Hydraulics Update Threshold= 0.02
Energy Slope Method= 1
Volume Change Method= 1
Sediment Retention Method= 0
XS Weighting Method= 0
Number of US Weighted Cross Sections= 1
Number of DS Weighted Cross Sections= 1
Upstream XS Weight=0
Main XS Weight=1
Downstream XS Weight=0
Number of DS XS's Weighted with US Boundary= 1
Upstream Boundary Weight= 1
Weight of XSs Associated with US Boundary= 0
Number of US XS's Weighted with DS Boundary= 1
Downstream Boundary Weight= 0.5
Weight of XSs Associated with DS Boundary= 0.5
Percentile Method= 0
Sediment Output Level= 3
Mass or Volume Output= 0
Output Increment Type= 1
Profile and TS Output Increment= 1
XS Output Flag= 0
XS Output Increment= 10
Write Gradation File= 0
Read Gradation Hotstart= 0
Write HDF5 File= 1
Write Binary Output= 1
Write DSS Sediment File= 0
SV Curve= 0
Specific Gage Flag= 0

--- MCMILLCK.f01 (steady flow) ---

Flow Title=Flow
Program Version=5.07
Number of Profiles= 6
Profile Names=f1p,f10p,f4p,f2p,f02p,f1pplus
River Rch & RM=BEECHRN1,Main            ,6099
     536     283     376     454     750     793
River Rch & RM=BEECHRN1,Main            ,4642
     659     350     465     559     919     975
River Rch & RM=COLDSPRBR,Main            ,7507
     515     271     361     436     721     762
River Rch & RM=COLDSPRBR,Main            ,7028
     574     303     403     486     802     849
River Rch & RM=COLDSPRBR,Main            ,2967
     657     349     463     557     916     972
River Rch & RM=COLDSPRBR,Main            ,1721
     734     392     518     623    1020    1090
River Rch & RM=HOGCMPRN,Main            ,4263
     557     294     391     472     779     824
River Rch & RM=HOGCMPRN,Main            ,3068
     638     338     449     540     889     943
River Rch & RM=JOBKNOBBR2,Main            ,1304
     458     240     321     387     643     678
River Rch & RM=JOBKNOBBR2,Main            ,794
     623     330     439     528     869     922
River Rch & RM=MCMILLCK,Main            ,13233
     571     302     401     483     798     844
River Rch & RM=MCMILLCK,Main            ,9424
     651     346     459     552     907     963
River Rch & RM=MCMILLCK,Main            ,7089
     735     392     519     624    1020    1090
River Rch & RM=MCMILLCK,Main            ,4416
     823     441     583     699    1140    1220
River Rch & RM=MIDDLEBR,Main            ,9120
     499     262     350     422     699     738
River Rch & RM=MIDDLEBR,Main            ,8068
     567     300     399     480     793     839
River Rch & RM=MIDDLEBR,Main            ,6306
     633     336     445     536     882     936
Boundary for River Rch & Prof#=BEECHRN1,Main            , 1
Up Type= 0
Dn Type= 3
Dn Slope=0.035
Boundary for River Rch & Prof#=BEECHRN1,Main            , 2
Up Type= 0
Dn Type= 3
Dn Slope=0.035
Boundary for River Rch & Prof#=BEECHRN1,Main            , 3
Up Type= 0
Dn Type= 3
Dn Slope=0.035
Boundary for River Rch & Prof#=BEECHRN1,Main            , 4
Up Type= 0
Dn Type= 3
Dn Slope=0.035
Boundary for River Rch & Prof#=BEECHRN1,Main            , 5
Up Type= 0
Dn Type= 3
Dn Slope=0.035
Boundary for River Rch & Prof#=BEECHRN1,Main            , 6
Up Type= 0
Dn Type= 3
Dn Slope=0.035
Boundary for River Rch & Prof#=COLDSPRBR,Main            , 1
Up Type= 0
Dn Type= 3
Dn Slope=0.036398
Boundary for River Rch & Prof#=COLDSPRBR,Main            , 2
Up Type= 0
Dn Type= 3
Dn Slope=0.036398
Boundary for River Rch & Prof#=COLDSPRBR,Main            , 3
Up Type= 0
Dn Type= 3
Dn Slope=0.036398
Boundary for River Rch & Prof#=COLDSPRBR,Main            , 4
Up Type= 0
Dn Type= 3
Dn Slope=0.036398
Boundary for River Rch & Prof#=COLDSPRBR,Main            , 5
Up Type= 0
Dn Type= 3
Dn Slope=0.036398
Boundary for River Rch & Prof#=COLDSPRBR,Main            , 6
Up Type= 0
Dn Type= 3
Dn Slope=0.036398
Boundary for River Rch & Prof#=HOGCMPRN,Main            , 1
Up Type= 0
Dn Type= 3
Dn Slope=0.02
Boundary for River Rch & Prof#=HOGCMPRN,Main            , 2
Up Type= 0
Dn Type= 3
Dn Slope=0.02
Boundary for River Rch & Prof#=HOGCMPRN,Main            , 3
Up Type= 0
Dn Type= 3
Dn Slope=0.02
Boundary for River Rch & Prof#=HOGCMPRN,Main            , 4
Up Type= 0
Dn Type= 3
Dn Slope=0.02
Boundary for River Rch & Prof#=HOGCMPRN,Main            , 5
Up Type= 0
Dn Type= 3
Dn Slope=0.02
Boundary for River Rch & Prof#=HOGCMPRN,Main            , 6
Up Type= 0
Dn Type= 3
Dn Slope=0.02
Boundary for River Rch & Prof#=JOBKNOBBR2,Main            , 1
Up Type= 0
Dn Type= 3
Dn Slope=0.043277
Boundary for River Rch & Prof#=JOBKNOBBR2,Main            , 2
Up Type= 0
Dn Type= 3
Dn Slope=0.043277
Boundary for River Rch & Prof#=JOBKNOBBR2,Main            , 3
Up Type= 0
Dn Type= 3
Dn Slope=0.043277
Boundary for River Rch & Prof#=JOBKNOBBR2,Main            , 4
Up Type= 0
Dn Type= 3
Dn Slope=0.043277
Boundary for River Rch & Prof#=JOBKNOBBR2,Main            , 5
Up Type= 0
Dn Type= 3
Dn Slope=0.043277
Boundary for River Rch & Prof#=JOBKNOBBR2,Main            , 6
Up Type= 0
Dn Type= 3
Dn Slope=0.043277
Boundary for River Rch & Prof#=MCMILLCK,Main            , 1
Up Type= 0
Dn Type= 3
Dn Slope=0.025
Boundary for River Rch & Prof#=MCMILLCK,Main            , 2
Up Type= 0
Dn Type= 3
Dn Slope=0.025
Boundary for River Rch & Prof#=MCMILLCK,Main            , 3
Up Type= 0
Dn Type= 3
Dn Slope=0.025
Boundary for River Rch & Prof#=MCMILLCK,Main            , 4
Up Type= 0
Dn Type= 3
Dn Slope=0.025
Boundary for River Rch & Prof#=MCMILLCK,Main            , 5
Up Type= 0
Dn Type= 3
Dn Slope=0.025
Boundary for River Rch & Prof#=MCMILLCK,Main            , 6
Up Type= 0
Dn Type= 3
Dn Slope=0.025
Boundary for River Rch & Prof#=MIDDLEBR,Main            , 1
Up Type= 0
Dn Type= 3
Dn Slope=0.083839
Boundary for River Rch & Prof#=MIDDLEBR,Main            , 2
Up Type= 0
Dn Type= 3
Dn Slope=0.083839
Boundary for River Rch & Prof#=MIDDLEBR,Main            , 3
Up Type= 0
Dn Type= 3
Dn Slope=0.083839
Boundary for River Rch & Prof#=MIDDLEBR,Main            , 4
Up Type= 0
Dn Type= 3
Dn Slope=0.083839
Boundary for River Rch & Prof#=MIDDLEBR,Main            , 5
Up Type= 0
Dn Type= 3
Dn Slope=0.083839
Boundary for River Rch & Prof#=MIDDLEBR,Main            , 6
Up Type= 0
Dn Type= 3
Dn Slope=0.083839
DSS Import GetInterval= 0
DSS Import GetPeak= 0
DSS Import FillOption= 0

--- MCMILLCK.g01 (geometry) ---

Geom Title=Geometry
Program Version=5.07

River Reach=MCMILLCK        ,Main
Reach XY= 30
 2080312.0378837414180.6490043852080520.12998718414460.660911545
2080949.93490186414664.7930492162081030.53086928414846.280875206
2081128.51492527414888.0790199642081169.35309818414765.194095135
2081214.54690543414874.4609369642081133.90992761414982.802911878
2081278.05793327414967.3429690452081227.43697152 415124.75800854
2081358.20409843415095.0651545382081364.54693353415398.771896213
2081709.30608651415450.771136045 2082091.0399031416009.853023127
2082835.99805886416246.0628525472083487.41112611416835.157146797
2083561.32895726417007.487838879 2083931.7291351 417319.37107338
2084454.31798494418165.2460220462084623.57092726418217.142899871
 2085081.6503917418703.0569542942085811.51146477418899.931888625
2086099.25006253419103.6821372962086461.58890477419401.677932382
 2086669.9618476419955.3641609552086884.58084095419961.551156461
2087388.18974185420591.5984527922087757.63421294420736.737270132
2087932.63419104421149.9319817872088069.26088628422213.085367292

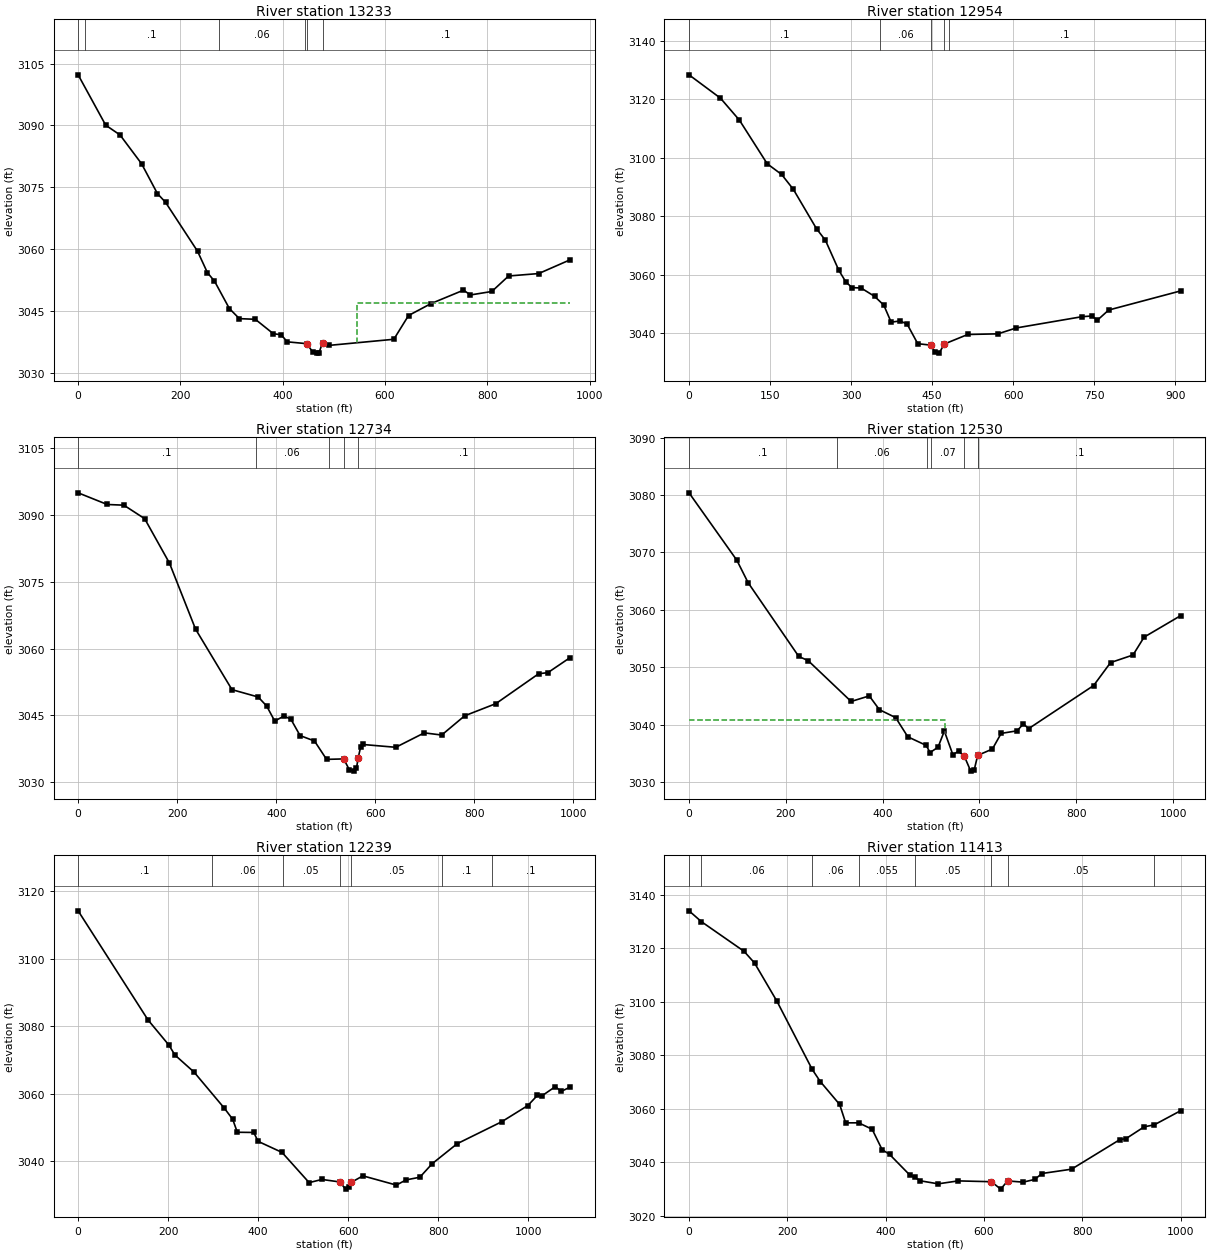
Type RM Length L Ch R = 1 ,13233   ,278.8,279,276.6
XS GIS Cut Line= 4
2079927.17612061 414439.836150052080316.08511969414189.724117458
2080503.40397078414071.0048667042080626.06219003413822.280954719
#Sta/Elev= 30
       0 3102.27    53.9 3090.05    81.9 3087.68   124.1 3080.68     155 3073.45
   170.9 3071.33   233.4 3059.47   252.8 3054.25   266.6  3052.2   295.7 3045.55
   315.2  3043.1   346.4 3042.94   381.5 3039.45   397.1 3039.18   408.8 3037.47
  446.943037.027   458.9 3034.97   467.3 3034.73   471.2 3034.88  477.763037.284
   490.6 3036.61   617.2 3038.09     646 3043.86   689.7 3046.74   753.4 3050.01
     767 3048.85   808.8 3049.69   841.6 3053.45   900.4 3054.04   961.5 3057.36
#Mann= 6 ,-1 , 0
       0     .06       0   13.74      .1       0  274.45     .06       0
  444.35      .1       0  446.94    .045       0  477.76      .1       0
#XS Ineff= 2 , 0
                          546.12         3046.88
Permanent Ineff=
       F       F
Bank Sta=446.94,477.76
XS Rating Curve= 0 ,0
Exp/Cntr=0.3,0.1

Type RM Length L Ch R = 1 ,12954   ,220.7,220.2,220.4
XS GIS Cut Line= 3
2080106.62818953414689.961962134 2080467.4115887414414.030099288
2080825.38823494414131.565113038
#Sta/Elev= 30
       0 3128.36    58.2 3120.37    93.3 3112.84   144.7 3097.93   171.4 3094.26
     193 3089.19     236 3075.68   252.4 3071.76   277.2 3061.48   290.2  3057.5
   301.6 3055.55   318.5 3055.41   343.3 3052.57   360.4 3049.57   374.1 3043.72
   390.5 3044.14   403.6 3043.08   423.3 3036.36  447.63 3035.86     456 3033.35
   462.9 3033.13   472.4 3036.24   515.8 3039.51   571.8 3039.73   605.5 3041.74
   727.7 3045.61   745.7 3045.83   755.7 3044.39   776.6 3047.87   910.2 3054.44
#Mann= 5 ,-1 , 0
       0      .1       0   353.6     .06       0  447.63    .045       0
   472.4     .06       0  481.47      .1       0
Bank Sta=447.63,472.4
XS Rating Curve= 0 ,0
Exp/Cntr=0.3,0.1

Type RM Length L Ch R = 1 ,12734   ,202.6,204.3,203.8
XS GIS Cut Line= 4
2080234.86973095414861.3809106352080560.15582576414602.536283955
2080774.70624968414407.3644302042080957.42045119414185.893088371
#Sta/Elev= 30
       0 3094.97    58.8 3092.35    92.3  3092.2   134.3 3089.17   184.4 3079.19
     237 3064.39   310.6 3050.79   363.5 3049.14   380.6 3047.12   396.9 3043.74
   415.6 3044.87   429.6 3044.14   448.1 3040.48   477.2 3039.26   501.6 3035.14
  536.213035.241   547.8 3032.74   557.5  3032.5   561.9  3033.1  565.213035.349
   570.4 3037.98   574.8 3038.48   641.3 3037.85   698.9 3041.09     734  3040.6
   780.4 3044.92   843.4 3047.65   929.9 3054.37   948.3  3054.6   992.9 3057.96
#Mann= 5 ,-1 , 0
       0      .1       0  358.83     .06       0  505.54      .1       0
  536.21    .045       0  565.21      .1       0
Bank Sta=536.21,565.21
XS Rating Curve= 0 ,0
Exp/Cntr=0.3,0.1

Type RM Length L Ch R = 1 ,12530   ,292.7,290.7,287.3
XS GIS Cut Line= 4
2080377.44195235414955.5063785462080670.89149669  414727.1141188
2080928.35226786414522.2529799642081155.36034402414303.549677208
#Sta/Elev= 30
       0 3080.39    98.8 3068.65   122.1 3064.74   226.8 3051.89     246 3051.18
   334.9 3044.06   372.4 3045.03   393.3 3042.63   426.9 3041.25     452 3037.91
   489.8 3036.42   498.1 3035.17   514.5  3036.1   527.5 3038.91   545.1 3034.79
   556.8 3035.41     5693034.491     582 3031.93   589.4 3032.21   596.4 3034.67
   626.8 3035.78   644.9  3038.5   677.8 3038.95     691 3040.17   701.5 3039.32
   835.9 3046.83   870.9 3050.83   917.3 3052.15   940.2 3055.26  1016.1 3059.02
#Mann= 7 ,-1 , 0
       0      .1       0  305.02     .06       0  491.31      .1       0
  498.98     .07       0     569    .045       0   596.4     .07       0
  597.04      .1       0
#XS Ineff= 2 , 0
          529.71 3040.78
Permanent Ineff=
       F       F
Bank Sta=569,596.4
XS Rating Curve= 0 ,0
Exp/Cntr=0.3,0.1

Type RM Length L Ch R = 1 ,12239   ,801,825.8,815
XS GIS Cut Line= 3
2080553.82152086415167.8983422072081032.75363386414780.323329955
2081391.26046276414466.110703796
#Sta/Elev= 30
       0 3114.23   155.3 3081.86   201.8 3074.38   215.1 3071.45   257.7 3066.37
   324.8 3055.69   343.4  3052.4   353.7 3048.54   390.1 3048.48   400.1 3045.83
   453.1 3042.56   513.3  3033.6   541.7 3034.54   581.4  3033.8   594.3 3031.67
   602.4 3032.23   607.1  3033.7   632.8 3035.61   707.1 3032.87   728.8 3034.41
   759.3  3035.2   786.7 3039.21   842.2 3045.14   941.1 3051.65   999.3 3056.47
  1020.7 3059.51  1030.2 3059.31  1060.3 3062.07  1073.4 3060.66  1092.8 3061.91
#Mann= 7 ,-1 , 0
       0      .1       0  297.82     .06       0  454.77     .05       0
   581.4    .045       0   607.1     .05       0  807.93      .1       0
  919.52      .1       0
Bank Sta=581.4,607.1
XS Rating Curve= 0 ,0
Exp/Cntr=0.3,0.1

Type RM Length L Ch R = 1 ,11413   ,343.6,349.3,339.9
XS GIS Cut Line= 3
2080774.70624968415361.0761054612081255.02254626415008.106010884
2081605.22427368414806.013239205
#Sta/Elev= 30
       0 3134.04    25.3 3129.97   111.9  3118.9   133.2 3114.54   178.9  3100.2
   250.6 3074.71     267 3070.18   306.4 3061.61   318.6 3054.73   345.1 3054.74
   372.5 3052.33   392.8  3044.7   407.8 3042.96   449.8 3035.08   459.4 3034.37
   470.2 3033.06   506.8 3031.92   547.5 3033.02  615.143032.713     634 3029.94
  648.043033.001   679.7 3032.56   703.6 3033.58   717.6 3035.78   778.1  3037.4
   876.7  3048.5   888.6 3048.79   925.9 3053.25   946.2 3053.97  1000.4 3059.31
#Mann= 8 ,-1 , 0
       0      .1       0    25.3     .06       0   250.6     .06       0
   345.1    .055       0   459.4     .05       0  615.14    .045       0
  648.04     .05       0   946.2      .1       0
Bank Sta=615.14,648.04
XS Rating Curve= 0 ,0
Exp/Cntr=0.5,0.3

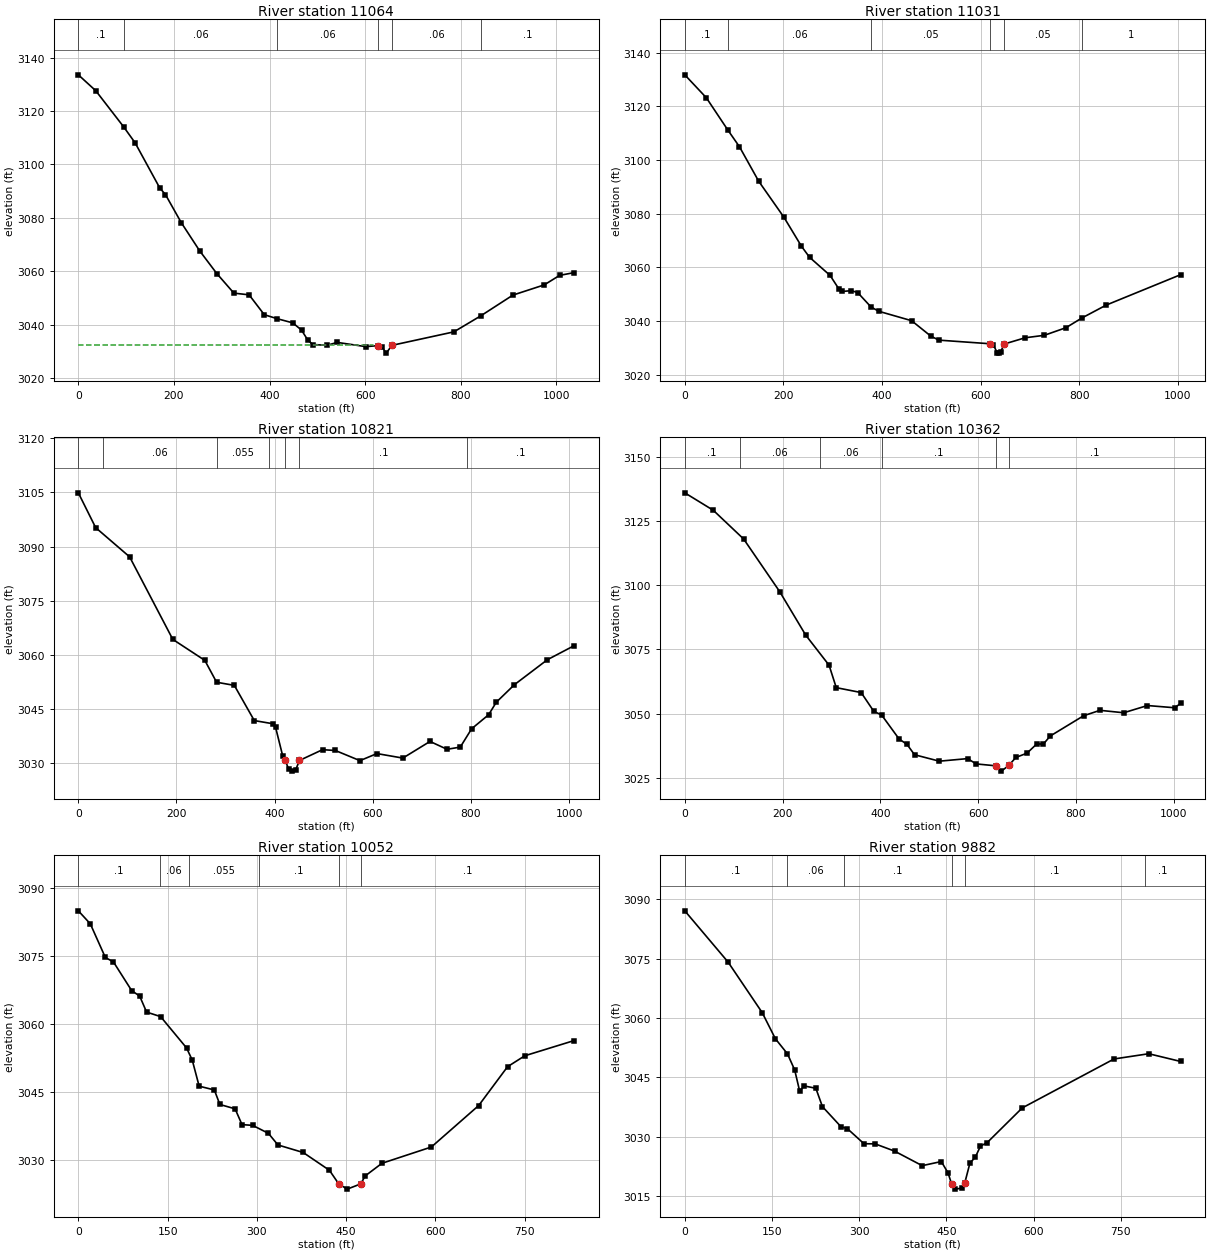
Type RM Length L Ch R = 1 ,11064   ,29.6,32.8,31.5
XS GIS Cut Line= 4
2080832.38063515415459.4434047742081267.28444702415162.348619706
2081403.30374621415062.1238729362081686.08071031414870.623017501
#Sta/Elev= 30
       0 3133.56    36.5  3127.6    94.8 3114.09   118.8 3108.09   170.4 3091.18
   182.2 3088.74   215.2 3078.25   253.9 3067.64   289.6 3059.17   325.4 3051.82
   357.2 3051.19     389 3043.75   415.9 3042.25   448.6 3040.69   466.9 3037.98
   479.6 3034.36   490.2 3032.59   519.8 3032.29   541.8 3033.37   601.4 3031.79
   627.23032.179   634.8 3031.72   644.2 3029.36   655.93032.266   785.6 3037.32
   841.8 3043.31   909.1 3051.09   974.6 3054.91  1006.8 3058.47  1037.2 3059.51
#Mann= 6 ,-1 , 0
       0      .1       0    94.8     .06       0   415.9     .06       0
   627.2    .045       0   655.9     .06       0   841.8      .1       0
#XS Ineff= 2 , 0
       0   617.2  3032.5   665.9       0  3032.5
Permanent Ineff=
       F       F
Bank Sta=627.2,655.9
XS Rating Curve= 0 ,0
Exp/Cntr(USF)=0,0
Exp/Cntr=0.5,0.3

Type RM Length L Ch R = 1 ,11031   ,215,209.9,210.3
XS GIS Cut Line= 3
2080844.90872849415470.1817704992081337.08382424415144.451343497
2081687.87043793414922.525118506
#Sta/Elev= 30
       0 3131.69    43.6 3123.16    86.7 3111.27   110.9 3104.87   149.8 3092.05
     201 3078.62   236.4 3067.85   252.9 3063.71   294.6 3056.94   312.4  3051.9
     319 3050.96   337.7 3051.27   350.5 3050.56   377.8 3045.14   393.7 3043.56
   459.9 3040.07   498.7 3034.34   515.2 3032.83   619.8 3031.47   625.4 3031.16
   633.2 3028.22     637 3027.99   640.9 3028.59   647.1 3031.35     690 3033.71
   728.9 3034.63   772.9 3037.47     805 3041.07   854.4 3045.89  1005.3 3057.22
#Mann= 6 ,-1 , 0
       0      .1       0    86.7     .06       0   377.8     .05       0
   619.8    .045       0   647.1     .05       0     805       1       0
Bank Sta=619.8,647.1
XS Rating Curve= 0 ,0
Exp/Cntr(USF)=0,0
Exp/Cntr=0.5,0.3

Type RM Length L Ch R = 1 ,10821   ,462.1,459.4,456.1
XS GIS Cut Line= 4
2080949.61961377415539.2873632162081091.68724301415452.432878122
 2081347.8425706415303.8071911342081813.48107502415015.761835456
#Sta/Elev= 30
       0  3104.9    35.3 3095.24   104.5 3087.13   192.5 3064.22   257.7  3058.4
   281.7 3052.33   317.8 3051.46   358.5 3041.69   397.4 3040.79   401.8 3039.85
   416.3 3031.93     421 3030.81   428.2 3028.33   435.1 3027.66   442.9 3028.03
   450.5 3030.62   497.5 3033.61   523.6 3033.39   573.8 3030.57   608.4 3032.53
   661.2 3031.28   716.5  3035.9   751.2 3033.72   778.2 3034.33   801.3 3039.41
     836 3043.32   851.5 3046.77   888.4 3051.64   955.6 3058.58  1010.2 3062.48
#Mann= 7 ,-1 , 0
       0      .1       0    50.3     .06       0  282.21    .055       0
  388.54      .1       0     421    .045       0   450.5      .1       0
  792.29      .1       0
Bank Sta=421,450.5
XS Rating Curve= 0 ,0
Exp/Cntr=0.3,0.1

Type RM Length L Ch R = 1 ,10362   ,310.4,310.2,298.5
XS GIS Cut Line= 3
2081181.66016018415810.9397070412081523.55678612415556.247631133
2082039.86218393415275.255739048
#Sta/Elev= 30
       0 3136.14    58.3 3129.32   120.4 3118.11   194.1 3097.58   247.3 3080.61
   295.1 3068.86   309.8  3060.1   360.7 3058.19   386.5 3050.88   402.7  3049.4
   438.4 3040.05   454.6 3037.94   469.9 3033.92   520.6  3031.4   578.7 3032.41
   595.7 3030.34   636.4 3029.59   647.6 3027.52   662.5 3029.72   677.4 3032.88
   699.9 3034.52     720 3038.14   733.6  3038.1   747.4 3041.21   815.8 3049.14
   849.3 3051.25   897.8  3050.3   946.3 3053.12  1002.4 3052.25  1014.2    3054
#Mann= 6 ,-1 , 0
       0      .1       0  112.02     .06       0  275.91     .06       0
  404.27      .1       0   636.4    .045       0   662.5      .1       0
Bank Sta=636.4,662.5
XS Rating Curve= 0 ,0
Exp/Cntr=0.3,0.1

Type RM Length L Ch R = 1 ,10052   ,170.6,169.4,167.3
XS GIS Cut Line= 2
2081533.24607119415993.6539085512082151.98203844415435.822675124
#Sta/Elev= 30
       0    3085    20.1 3082.14    45.4 3074.72      59 3073.74    89.6 3067.43
   103.1 3066.21   114.7 3062.69   138.2  3061.7   181.8  3054.8   191.4 3052.12
     203 3046.37   228.5 3045.54   237.8 3042.34   263.4 3041.38     275  3037.9
   292.8 3037.74   319.3 3035.99   335.4 3033.42   377.8 3031.76   421.9 3027.84
   437.6 3024.83   451.8 3023.69   474.8 3024.86   481.7 3026.57   510.1 3029.38
   593.2 3032.97   672.7 3042.11   721.2 3050.66   750.2 3053.07   833.1 3056.42
#Mann= 6 ,-1 , 0
       0      .1       0  136.55     .06       0   185.9    .055       0
   304.1      .1       0   437.6    .045       0   474.8      .1       0
Bank Sta=437.6,474.8
XS Rating Curve= 0 ,0
Exp/Cntr=0.3,0.1

Type RM Length L Ch R = 1 ,9882    ,71.3,72.3,72.9
XS GIS Cut Line= 2
2081660.59227318416116.8472317162082279.32791236415529.947814956
#Sta/Elev= 30
       0 3087.09    74.4 3074.15   133.2 3061.35   155.8 3054.77   176.6 3050.95
     189 3046.88   197.5 3041.57   205.6 3042.84   225.4 3042.25   236.7 3037.62
   268.9  3032.5   279.6 3032.05   308.2 3028.24   327.3 3028.21   360.7 3026.38
   408.3  3022.7   441.2 3023.74   452.8 3020.86   458.8 3018.12   465.5 3016.77
   476.9 3017.04   481.4 3018.25   490.5  3023.4   499.5 3024.78   508.5 3027.63
   520.1 3028.53   580.4 3037.29   738.3 3049.66     798 3050.98   852.8 3049.03
#Mann= 6 ,-1 , 0
       0      .1       0  175.51     .06       0  273.96      .1       0
   458.8    .045       0   481.4      .1       0  792.07      .1       0
Bank Sta=458.8,481.4
XS Rating Curve= 0 ,0
Exp/Cntr=0.3,0.1

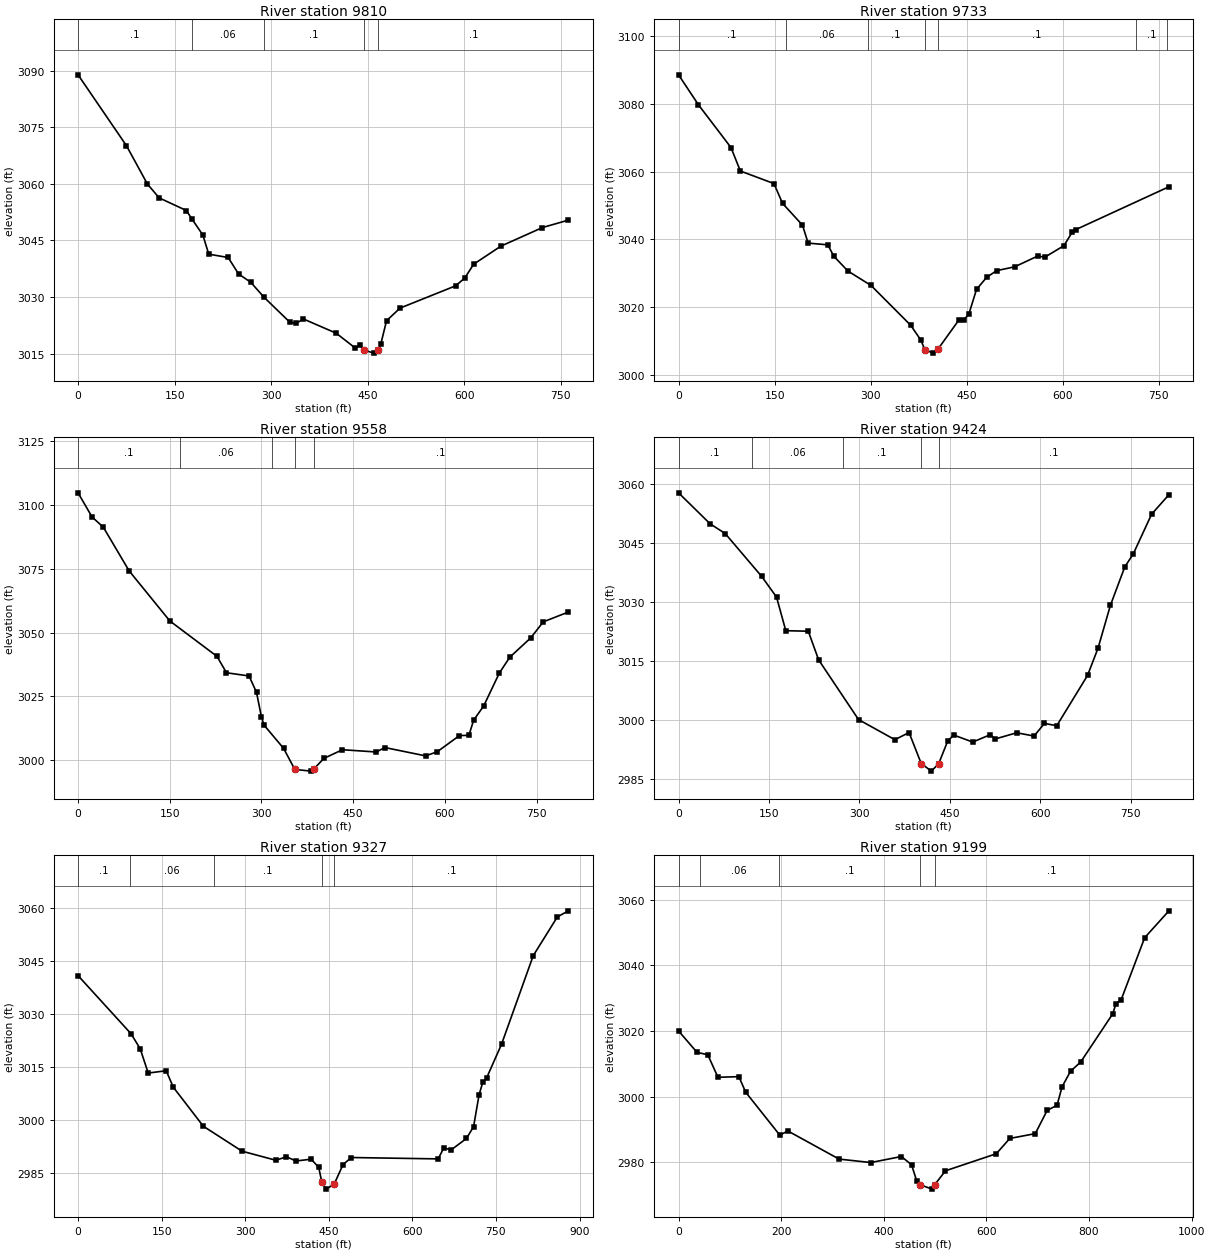
Type RM Length L Ch R = 1 ,9810    ,76.7,76.8,76.3
XS GIS Cut Line= 4
2081712.69237681416163.8185906652081993.53662584415891.056190533
2082101.63135478415805.1865460472082275.39110597415650.621185972
#Sta/Elev= 30
       0  3088.9    75.2 3070.11   107.8 3059.93   126.1 3056.26   168.3 3052.92
   176.4  3050.8   193.9 3046.44   203.1 3041.34   233.3 3040.46   249.4  3036.1
   268.3  3033.9     289 3029.92   329.5 3023.23   338.9 3022.98   350.2 3024.16
   401.2 3020.38   430.8 3016.45   437.8 3017.19   444.8 3015.94   459.2  3015.1
   466.8 3016.04   470.5 3017.52   479.4 3023.69   500.4 3027.04   586.8 3032.95
   600.9    3035   614.8 3038.68     657 3043.46   721.7  3048.4   762.1 3050.38
#Mann= 5 ,-1 , 0
       0      .1       0   176.4     .06       0     289      .1       0
   444.8    .045       0   466.8      .1       0
Bank Sta=444.8,466.8
XS Rating Curve= 0 ,0
Exp/Cntr(USF)=0,0
Exp/Cntr=0.3,0.1

Type RM Length L Ch R = 1 ,9733    ,179.1,175,170.6
XS GIS Cut Line= 4
2081758.87029186416192.977984965 2082068.9300392415909.217725709
 2082114.6363126415841.4248822932082319.46989244415675.288731635
#Sta/Elev= 30
       0 3088.54      31 3079.72    81.9 3067.08    96.5 3060.16     149 3056.45
   162.4 3050.61   193.5 3044.19   202.4 3038.88   233.1 3038.38   242.4 3035.02
   264.6 3030.63   300.6 3026.39   362.5 3014.65   378.4 3010.26   384.7 3007.41
   397.8 3006.42   404.9 3007.54   437.6 3016.15   445.5 3016.24   453.4 3017.98
   465.3 3025.21   481.1 3028.78   496.8 3030.76   524.9 3031.89   561.5 3035.12
   571.5 3034.68   601.8 3038.12   615.1 3042.22   620.5 3042.88   765.8 3055.51
#Mann= 7 ,-1 , 0
       0      .1       0  167.11     .06       0   295.1      .1       0
   384.7    .045       0   404.9      .1       0  713.83      .1       0
  763.35      .1       0
Bank Sta=384.7,404.9
XS Rating Curve= 0 ,0
Exp/Cntr=0.3,0.1

Type RM Length L Ch R = 1 ,9558    ,139.5,134.2,128.9
XS GIS Cut Line= 2
2081958.19436827416368.770940468 2082388.6793997415691.898934633
#Sta/Elev= 30
       0 3104.76    22.9 3095.29    41.3  3091.3    83.6 3074.15   150.2 3054.53
   227.2 3040.68   242.8 3034.24   279.7 3032.99   291.9 3026.57   299.9 3017.03
   304.2 3013.73   336.1 3004.65   354.6 2996.36   380.7 2995.69   385.5 2996.48
   402.1 3000.67   432.5 3004.08   487.7 3003.19   501.9 3004.93   568.5 3001.67
   587.5 3003.27   623.8 3009.61   639.4 3009.74   647.1 3015.66   663.5 3021.21
   689.3  3034.2   706.3 3040.34   740.5 3047.91     761 3054.19   802.2 3058.05
#Mann= 5 ,-1 , 0
       0      .1       0  166.86     .06       0  316.53      .1       0
   354.6    .045       0   385.5      .1       0
Bank Sta=354.6,385.5
XS Rating Curve= 0 ,0
Exp/Cntr=0.3,0.1

Type RM Length L Ch R = 1 ,9424    ,95.6,97.2,96.8
XS GIS Cut Line= 4
2082131.21895662416478.122427791 2082275.1753616416129.305212051
 2082291.7858927416053.1741307082082392.83227852415709.893649295
#Sta/Elev= 30
       0  3057.7    52.4 3049.82    77.3 3047.37   137.6 3036.51   162.5 3031.22
   177.8 3022.69   215.1 3022.55   232.3 3015.27   298.4 3000.12   358.7    2995
   382.2 2996.82  402.372988.947   419.2 2987.02   431.3  2988.9     446 2994.55
   456.1 2996.19   487.8  2994.4   516.9 2996.28   524.8 2995.18   560.7 2996.76
   589.5 2995.93   606.7 2999.14   627.1 2998.55   678.1 3011.31   695.5 3018.23
     716  3029.1     740 3038.93   753.7  3042.1   784.4 3052.28   813.1 3057.22
#Mann= 5 ,-1 , 0
       0      .1       0  121.47     .06       0  273.04      .1       0
  402.37    .045       0   431.3      .1       0
Bank Sta=402.37,431.3
XS Rating Curve= 0 ,0
Exp/Cntr=0.3,0.1

Type RM Length L Ch R = 1 ,9327    ,129,127.5,125.5
XS GIS Cut Line= 5
2082205.64334843416531.6511921292082277.94372877416406.144225299
2082348.53774768416210.9726996272082374.14990118416118.791125461
2082458.49782962415695.039676383
#Sta/Elev= 30
       0 3040.75      95 3024.33   111.5 3020.07   125.9  3013.2   158.2 3013.85
   170.8 3009.22   224.8 2998.16   294.3  2991.1   355.1 2988.53   373.9 2989.53
     391 2988.33   418.3 2988.83   431.9 2986.54  437.56 2982.27   445.5 2980.37
   459.8 2981.83   475.6 2987.33   490.5 2989.31   646.3 2988.92   656.3 2991.99
   669.7 2991.48     697 2994.69   709.8 2998.03   719.8 3007.13   726.5 3010.65
   733.2 3011.81     760 3021.34   816.9  3046.4   860.3 3057.38   880.1 3059.08
#Mann= 5 ,-1 , 0
       0      .1       0   92.37     .06       0  243.24      .1       0
  437.56    .045       0   459.8      .1       0
Bank Sta=437.56,459.8
XS Rating Curve= 0 ,0
Exp/Cntr=0.3,0.1

Type RM Length L Ch R = 1 ,9199    ,169.6,172.5,175.4
XS GIS Cut Line= 4
2082341.61682978416611.0053641352082486.95741835416224.814535454
2082518.79396886415945.2068269552082517.40978527415683.593833134
#Sta/Elev= 30
       0 3020.02      36 3013.49      57 3012.76    76.8 3005.89   117.6 3006.09
   130.7 3001.38   197.3 2988.27   213.1 2989.53   312.9 2980.96   374.8 2979.91
   434.3 2981.75   454.1 2979.23     464 2974.39  471.062973.167   493.7 2971.81
     499 2973.11   520.2  2977.4   619.2 2982.59   645.6 2987.26   695.2 2988.72
   718.4 2995.81   737.6 2997.37   747.5 3003.02     764 3007.75   783.7 3010.54
   846.1 3025.22   852.6 3028.33   862.5 3029.48   908.4 3048.43   955.7 3056.62
#Mann= 5 ,-1 , 0
       0      .1       0   41.34     .06       0  195.43      .1       0
  471.06    .045       0     499      .1       0
Bank Sta=471.06,499
XS Rating Curve= 0 ,0
Exp/Cntr=0.3,0.1

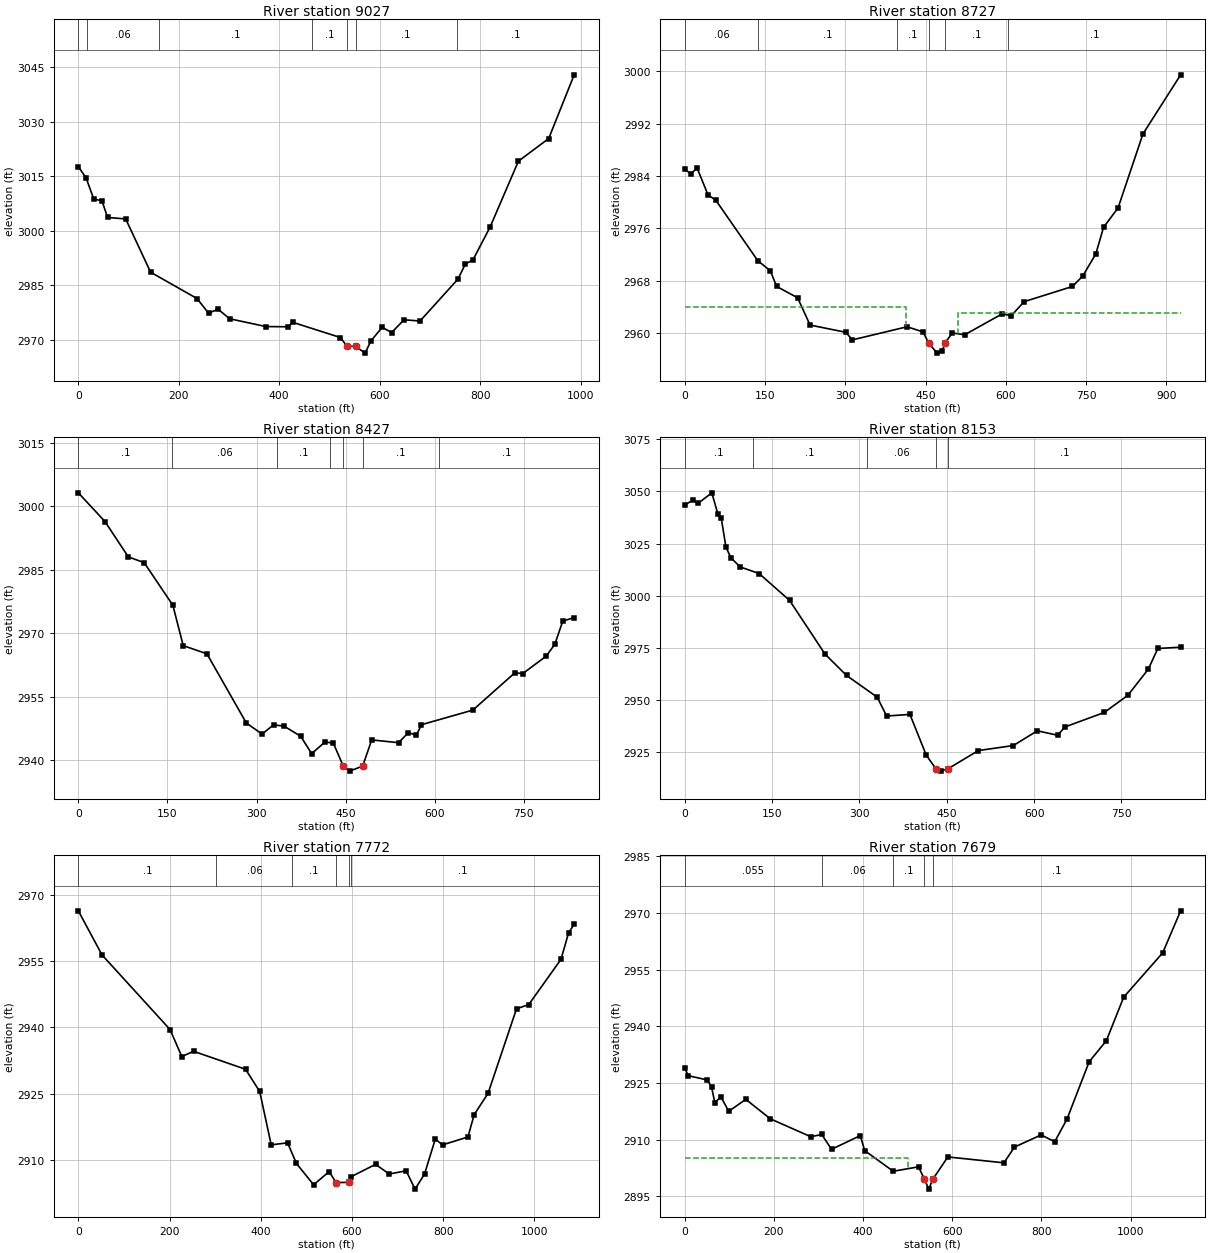
Type RM Length L Ch R = 1 ,9027    ,297.6,300,299.8
XS GIS Cut Line= 3
2082386.34344634416633.3580097112082661.45116386416166.173904717
2082880.37854752 415778.55525738
#Sta/Elev= 30
       0 3017.64    15.6 3014.47    30.8 3008.67    46.9 3008.27    58.3 3003.64
    94.3 3003.23   143.9 2988.58   236.4 2981.32   259.2 2977.31   278.3 2978.39
   301.1 2975.77   373.5 2973.62   417.8 2973.56   426.8 2974.79   521.9  2970.6
   535.2 2968.15     552 2968.19   571.1 2966.31   582.4 2969.64     605  2973.4
   623.9 2971.98   648.6 2975.49   680.4 2975.14   755.8 2986.66   770.8 2990.86
   785.6 2991.91   819.8 3000.97   876.3 3019.13   936.6 3025.35   987.3 3042.88
#Mann= 7 ,-1 , 0
       0      .1       0   18.08     .06       0  160.98      .1       0
  466.03      .1       0   535.2    .045       0     552      .1       0
  753.14      .1       0
Bank Sta=535.2,552
XS Rating Curve= 0 ,0
Exp/Cntr=0.3,0.1

Type RM Length L Ch R = 1 ,8727    ,294.8,300,302.2
XS GIS Cut Line= 3
2082662.15982386416701.5796580462082919.15996602416305.209059715
2083160.27693784415920.476889551
#Sta/Elev= 30
       0 2985.02    11.3 2984.33      23 2985.22    43.3 2981.13    58.2 2980.27
   136.4 2971.05   159.9  2969.5   171.6 2967.11   210.7 2965.39   234.1 2961.21
   300.6 2960.11   313.3 2958.95   415.3 2960.95   445.3 2960.16   455.6 2958.45
   471.5 2956.92   480.4 2957.18   486.5 2958.49   499.8    2960     523 2959.73
   592.7 2962.91   610.2 2962.66     634 2964.79   724.3 2967.11   743.7 2968.73
     768  2972.1   782.4 2976.16   809.5 2979.12     856 2990.43   926.4 2999.47
#Mann= 6 ,-1 , 0
       0     .06       0  136.67      .1       0  397.01      .1       0
   455.6    .045       0   486.5      .1       0  603.88      .1       0
#XS Ineff= 2 , 0
          413.13 2963.94   509.9         2963.07
Permanent Ineff=
       F       F
Bank Sta=455.6,486.5
XS Rating Curve= 0 ,0
Exp/Cntr=0.3,0.1

Type RM Length L Ch R = 1 ,8427    ,274.6,274.2,269.5
XS GIS Cut Line= 4
2082798.69235918416848.7598098812083118.04703543416520.971095383
2083215.04487294416433.8282250462083380.00845379416250.436531454
#Sta/Elev= 30
       0 3003.22    44.8 2996.44    84.2 2988.07   110.8 2986.72   159.1 2976.65
   176.6  2967.1   216.5 2965.16   282.8 2948.81   309.3 2946.19   328.6 2948.36
   346.4 2948.07   374.3 2945.67   392.8 2941.57   415.6 2944.36   429.4 2944.01
   446.2 2938.56   456.9 2937.43   478.7 2938.63   493.9 2944.81   539.1 2944.15
   555.7 2946.55   568.9 2945.87   577.7 2948.41   664.2 2951.86   734.8 2960.67
   748.2 2960.49   787.8 2964.63   802.2 2967.44   815.5 2972.89   834.7 2973.74
#Mann= 7 ,-1 , 0
       0      .1       0  158.35     .06       0  334.62      .1       0
   423.8      .1       0   446.2    .045       0   478.7      .1       0
  607.34      .1       0
Bank Sta=446.2,478.7
XS Rating Curve= 0 ,0
Exp/Cntr=0.3,0.1

Type RM Length L Ch R = 1 ,8153    ,386.7,380.9,377.3
XS GIS Cut Line= 3
2083049.16167453417067.5434930472083318.24578202416698.186620206
2083544.28634045416374.553409204
#Sta/Elev= 30
       0 3043.53    13.9 3045.83    22.7 3044.27    46.4 3049.36      57 3039.02
    62.6 3037.16    70.7 3023.24    79.2 3018.15    95.1 3013.76   127.6  3010.6
     180 2997.68   240.8 2971.91   277.8 2961.62   330.5  2951.2   346.7 2942.13
   386.7 2942.91   414.8 2923.31     432 2916.51   440.7 2915.66  452.572916.877
   504.2 2925.53   564.4 2927.96   605.5 2935.03   640.5  2932.9     653 2936.88
   720.5 2943.83   761.1  2952.1   796.2 2964.65   812.5 2974.58   851.7  2975.2
#Mann= 5 ,-1 , 0
       0      .1       0  117.15      .1       0  313.06     .06       0
     432    .045       0  452.57      .1       0
Bank Sta=432,452.57
XS Rating Curve= 0 ,0
Exp/Cntr=0.3,0.1

Type RM Length L Ch R = 1 ,7772    ,92.7,92.4,91.3
XS GIS Cut Line= 4
2083279.08540278417498.3161330582083501.57687554 417058.12188756
2083573.90323405 416926.260770232083670.44553694416493.348775297
#Sta/Elev= 30
       0 2966.42    51.9 2956.43   201.2  2939.5   226.9 2933.39   252.6 2934.58
   366.6 2930.51   397.7 2925.47   422.9 2913.38   458.8 2913.83   478.3 2909.15
   515.9 2904.33     550 2907.31  565.12 2904.83   592.6 2904.87   596.9 2906.09
   651.6 2908.95   681.8 2906.77   718.8 2907.49   738.3 2903.34   759.1 2906.76
   782.7 2914.68   798.6 2913.37   854.3 2915.16     868 2920.24   898.3 2925.03
   960.8 2944.21   987.7 2945.18  1058.3 2955.42  1075.1 2961.46  1087.2 2963.36
#Mann= 6 ,-1 , 0
       0      .1       0   302.9     .06       0   469.1      .1       0
  565.12    .045       0   592.6      .1       0   596.9      .1       0
Bank Sta=565.12,592.6
XS Rating Curve= 0 ,0
Exp/Cntr=0.5,0.3

Type RM Length L Ch R = 1 ,7679    ,62.3,54,54.1
XS GIS Cut Line= 5
2083493.26839787417581.3272423742083602.61988518417095.474211454
 2083609.5408031417017.9592746352083617.84623268416919.681255966
2083710.58718893416491.964591712
#Sta/Elev= 30
       0 2928.86     7.9 2926.89    50.5 2925.76    60.1 2923.87    67.4  2919.7
    80.8 2921.35    98.5 2917.47   136.9 2920.63   191.8 2915.48   282.6 2910.74
   307.1 2911.33   329.1 2907.41   393.6 2911.03   403.6 2907.06   467.5  2901.6
   524.2 2902.77   537.3 2899.56   547.2 2896.87  556.27 2899.49     590 2905.39
   715.9 2903.83   739.4    2908   799.3 2911.22   829.6 2909.41   857.2 2915.39
   906.9 2930.57   945.5 2936.16   984.5  2947.7  1071.8 2959.39  1112.1 2970.53
#Mann= 5 ,-1 , 0
       0    .055       0   307.1     .06       0   467.5      .1       0
   537.3    .045       0  556.27      .1       0
#XS Ineff= 3 ,-1
       0     500    2905     500   522.3  2901.8   571.9     800  2901.8
Permanent Ineff=
       F       F       F
Bank Sta=537.3,556.27
XS Rating Curve= 0 ,0
Exp/Cntr=0.5,0.3