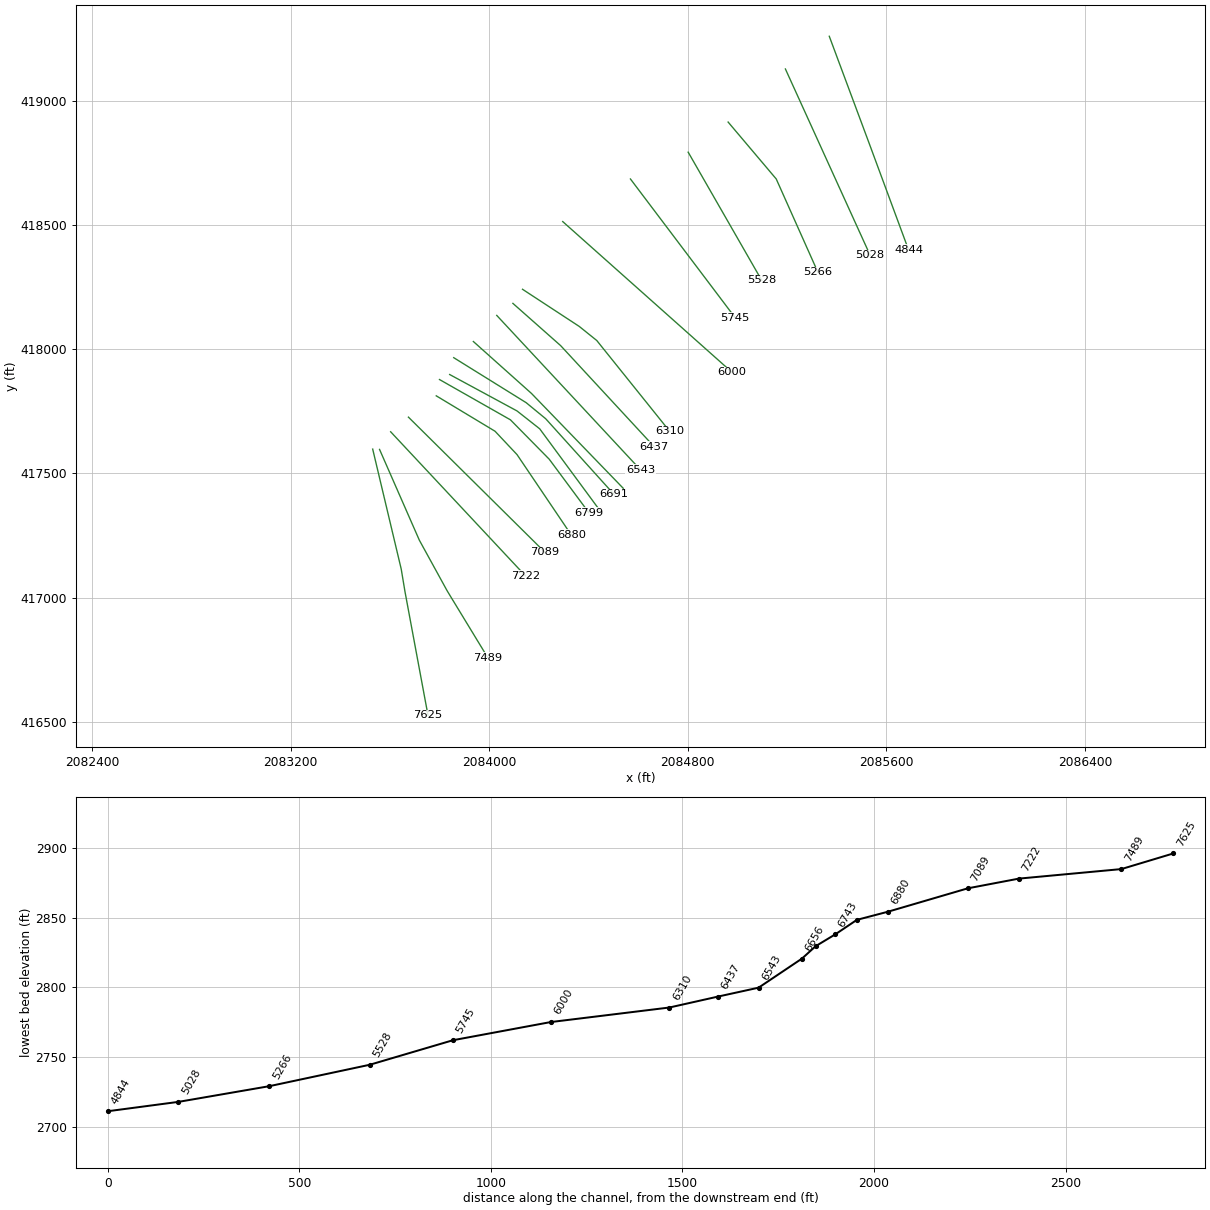
HEC-RAS study MCMILLCK.prj: MCMILLCK

--- MCMILLCK.g01 (geometry) --- (continued)

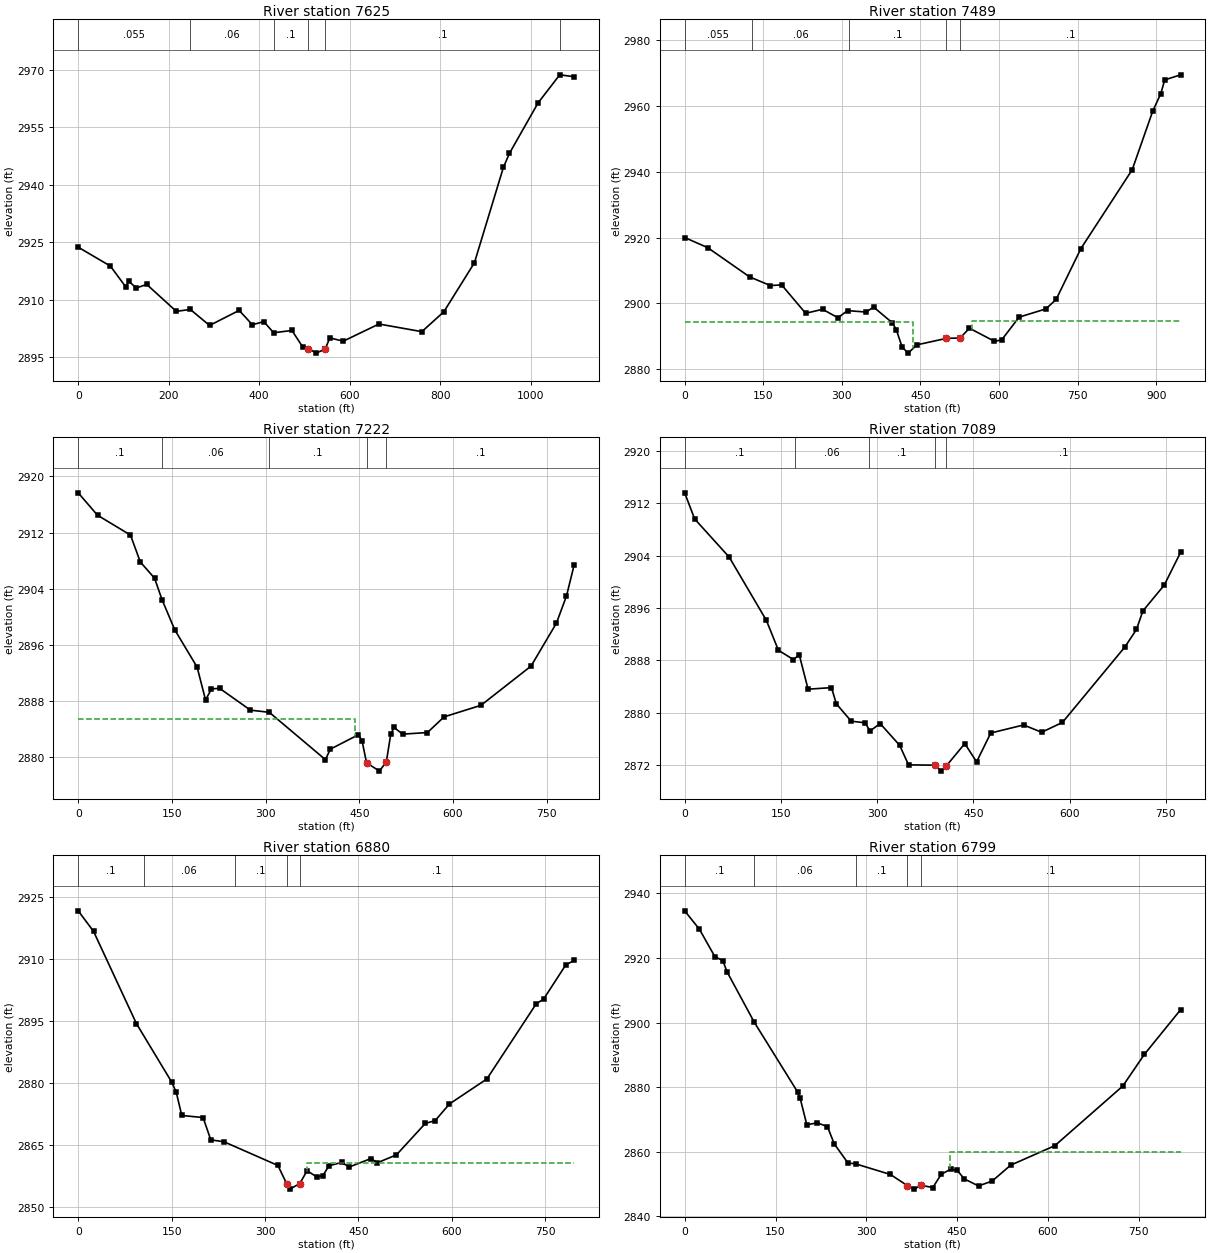
Type RM Length L Ch R = 1 ,7625    ,127.8,136,139.3
XS GIS Cut Line= 4
2083530.64168268417597.9374453722083645.52990437417114.853109717
2083660.75625187417023.4960089622083753.49720812416525.185325801
#Sta/Elev= 30
       0  2923.7    71.1 2918.77   104.9 2913.37   111.6 2914.81   128.5 2913.06
   151.4 2913.99   216.8 2906.96   247.7 2907.46   290.3 2903.28   355.7 2907.21
   384.8 2903.47   410.2 2904.27   431.9 2901.38   472.4 2901.97     496 2897.68
   508.8 2897.25     526 2896.06   545.9 2897.12   545.9 2897.14   555.9 2900.03
   585.8 2899.18   664.6 2903.66   759.4 2901.66   808.1 2906.86   875.6 2919.64
   939.6 2944.51   952.9 2948.16  1016.3 2961.35  1064.1 2968.67    1096 2968.18
#Mann= 6 ,-1 , 0
       0    .055       0   247.7     .06       0   431.9      .1       0
   508.8    .045       0   545.9      .1       0  1064.1      .1       0
Bank Sta=508.8,545.9
XS Rating Curve= 0 ,0
Exp/Cntr=0.5,0.3

Type RM Length L Ch R = 1 ,7489    ,262.7,267.4,268.9
XS GIS Cut Line= 4
2083558.32568243417596.5532618022083718.53466204417231.109290219
2083831.00679424417026.3775759222083994.22089158416758.143451511
#Sta/Elev= 30
       0 2919.99    44.1  2916.9   123.8 2908.03   163.6 2905.38   185.1 2905.58
   230.9 2896.95   263.2 2898.16   292.6 2895.59   310.8 2897.76   346.3 2897.32
   360.6 2898.83   396.4 2894.05   403.8 2892.01     415 2886.69   426.3 2884.83
   443.7 2887.37   499.4 2889.31   525.8 2889.45   543.5 2892.41     591 2888.45
   604.8 2888.81   638.4 2895.78   689.4 2898.28     709 2901.16   756.3 2916.64
   854.2 2940.62   893.3 2958.41   908.7 2963.74   916.3 2967.94   946.6 2969.48
#Mann= 5 ,-1 , 0
       0    .055       0  128.44     .06       0  313.73      .1       0
   499.4    .045       0   525.8      .1       0
#XS Ineff= 2 , 0
          435.17  2894.4  548.85         2894.74
Permanent Ineff=
       F       F
Bank Sta=499.4,525.8
XS Rating Curve= 0 ,0
Exp/Cntr=0.3,0.1

Type RM Length L Ch R = 1 ,7222    ,128,133.4,137.8
XS GIS Cut Line= 2
2083602.91377588417667.7894182932084145.40788281417087.916760234
#Sta/Elev= 30
       0 2917.66    30.9 2914.47    83.7 2911.64    99.4 2907.81   122.2  2905.5
   134.2 2902.44   154.5 2898.15   190.4 2892.82   203.9 2888.14   213.4 2889.72
   226.4  2889.8   275.8 2886.69     306 2886.38   395.9 2879.63   403.5 2881.12
   448.7 2883.19   454.5 2882.31  461.672879.197   482.3    2878   493.42879.336
   500.4 2883.23   505.6 2884.23   519.5 2883.27   559.2  2883.5   585.8 2885.73
   644.9 2887.38   725.1 2892.97   765.7 2899.09   781.8 2902.95   794.1 2907.39
#Mann= 5 ,-1 , 0
       0      .1       0   134.2     .06       0     306      .1       0
  461.67    .045       0   493.4      .1       0
#XS Ineff= 2 , 0
          442.96 2885.48
Permanent Ineff=
       F       F
Bank Sta=461.67,493.4
XS Rating Curve= 0 ,0
Exp/Cntr(USF)=0,0
Exp/Cntr=0.3,0.1

Type RM Length L Ch R = 1 ,7089    ,209.8,208.4,208.7
XS GIS Cut Line= 2
 2083674.5980877417726.667830959 2084224.1242196417182.678761467
#Sta/Elev= 30
       0  2913.6    15.5 2909.61    69.4 2903.77   127.4 2894.09   146.1 2889.53
   169.4 2888.11   178.7  2888.8   192.4 2883.57   228.9 2883.81   236.4 2881.34
   259.6 2878.68   281.3 2878.43   288.9 2877.17   304.7 2878.32   335.1    2875
     349    2872   390.5 2871.95   399.7 2871.04   408.1 2871.86   436.7 2875.25
   455.1 2872.46   477.2 2876.87   528.5  2878.1   556.5 2876.98     589 2878.49
   686.5 2890.05   704.4 2892.71   714.3 2895.53   747.7 2899.49   773.2 2904.51
#Mann= 5 ,-1 , 0
       0      .1       0  172.69     .06       0  286.79      .1       0
   390.5    .045       0   408.1      .1       0
Bank Sta=390.5,408.1
XS Rating Curve= 0 ,0
Exp/Cntr=0.3,0.1

Type RM Length L Ch R = 1 ,6880    ,80.5,81.1,81.1
XS GIS Cut Line= 4
2083786.71794218417812.4881973712084023.41563153417669.915647879
2084112.00436512417575.7905080472084330.70733976417251.888596788
#Sta/Elev= 30
       0 2921.71    24.6 2916.74    93.5 2894.38   150.4 2880.15   157.5 2877.71
   166.3 2872.13   200.5 2871.62   212.9 2866.22     234 2865.76   320.7 2860.01
     335 2855.51   339.8 2854.28   355.9 2855.64   367.5 2858.74   382.9 2857.25
   393.1 2857.58   402.6 2859.93   422.8 2860.75   435.4 2859.65   470.3  2861.7
   480.3 2860.66     511 2862.58   557.4  2870.2   573.2 2870.88   596.1 2874.91
   656.3 2880.98   735.5 2899.19   747.4 2900.33     783 2908.62   796.4 2909.68
#Mann= 5 ,-1 , 0
       0      .1       0   104.9     .06       0  251.88      .1       0
     335    .045       0   355.9      .1       0
#XS Ineff= 2 , 0
                          366.61          2860.6
Permanent Ineff=
       F       F
Bank Sta=335,355.9
XS Rating Curve= 0 ,0
Exp/Cntr=0.3,0.1

Type RM Length L Ch R = 1 ,6799    ,54.6,56.4,60.6
XS GIS Cut Line= 4
2083799.68435919 417878.132658632084085.42288498417715.876126238
2084241.71410368 417557.198782062084401.17719552417342.162199922
#Sta/Elev= 30
       0 2934.55    24.4 2928.84    49.8 2920.39    63.1 2919.12    69.7 2915.77
   114.9 2900.09   186.6 2878.47   190.4 2876.79   201.7 2868.35   218.9 2868.96
   235.7 2867.81     247 2862.45   269.6 2856.55   282.3 2856.27   339.7 2852.99
   367.7 2849.54   379.4 2848.45   389.9 2849.64   409.8 2848.95   423.8 2853.07
   439.3  2854.6   450.2 2854.22   461.8 2851.61   485.3 2849.43     508 2850.97
   538.3 2855.86   611.3 2861.89   723.5 2880.34   759.1 2890.13     819 2903.96
#Mann= 5 ,-1 , 0
       0      .1       0   114.9     .06       0   282.3      .1       0
   367.7    .045       0   389.9      .1       0
#XS Ineff= 2 , 0
                           438.6         2859.97
Permanent Ineff=
       F       F
Bank Sta=367.7,389.9
XS Rating Curve= 0 ,0
Exp/Cntr(USF)=0,0
Exp/Cntr=0.3,0.1

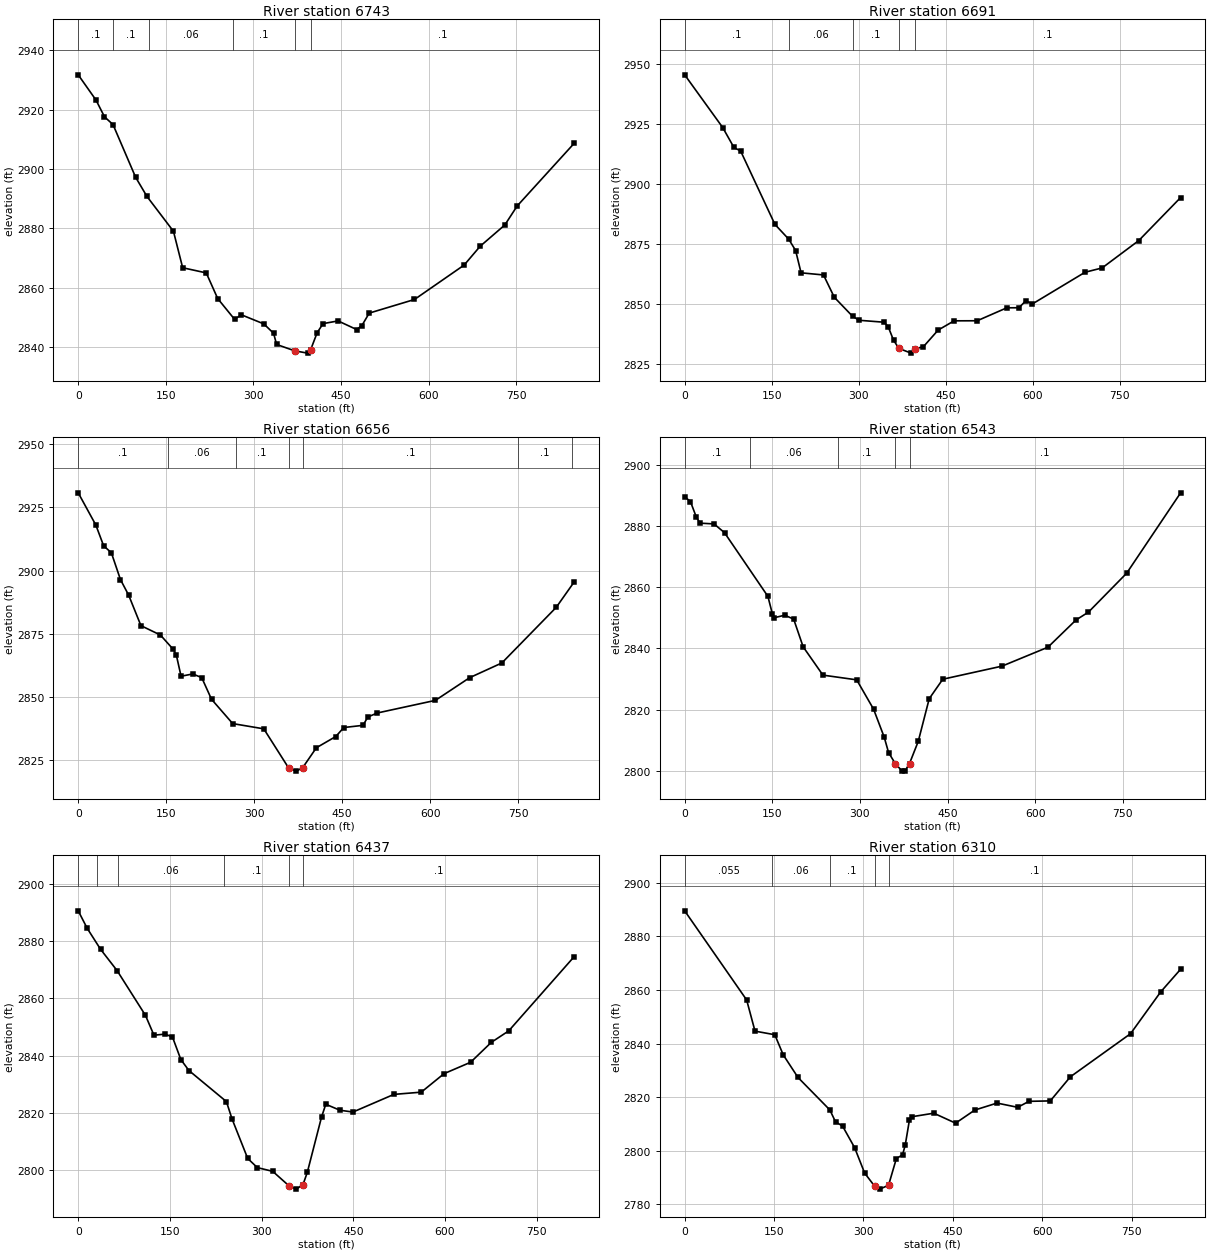
Type RM Length L Ch R = 1 ,6743    ,56.2,51.3,56.1
XS GIS Cut Line= 4
2083840.70175812417898.3082357052084112.00436512 417751.58346355
2084203.36113778417679.6052610432084455.28484651417337.708635122
#Sta/Elev= 30
       0 2931.67    30.5 2923.17      45 2917.55    59.6 2914.94    98.3 2897.23
   117.7 2890.78   163.1 2879.05   178.9 2866.79   219.3 2865.05   238.9 2856.42
   267.7 2849.46   279.6 2850.95   317.9  2847.9   334.6 2844.75   339.8 2840.98
  370.822838.845   392.8 2838.07   398.2 2839.26   409.3 2844.97   419.4    2848
   445.1  2848.9   476.9    2846   485.8 2847.32   498.4 2851.53   575.9 2856.11
     661 2867.69   688.5 2874.03   730.7 2881.18   751.8 2887.56   849.4 2908.63
#Mann= 6 ,-1 , 0
       0      .1       0   60.15      .1       0  120.38     .06       0
  264.45      .1       0  370.82    .045       0   398.2      .1       0
Bank Sta=370.82,398.2
XS Rating Curve= 0 ,0
Exp/Cntr=0.3,0.1

Type RM Length L Ch R = 1 ,6691    ,39.2,35.7,35.5
XS GIS Cut Line= 4
2083857.06155569417966.1584084682084148.69911391  417784.9896223
2084227.50017131417720.1812760282084502.19918449 417416.02392364
#Sta/Elev= 30
       0 2945.56    65.6 2923.59    84.9  2915.3    96.5  2913.8   155.6 2883.23
   179.4 2877.07   191.3 2872.34   200.7 2863.04   239.4 2862.15     258 2852.85
   289.6  2844.9   300.9 2843.26   343.8 2842.45   350.8 2840.65   360.1 2834.99
   369.4 2831.53   390.4 2829.57  397.662831.429   411.6 2832.23   437.1 2839.18
   464.6 2843.03   504.4 2843.06   555.5 2848.46   576.4 2848.48   588.4 2851.42
   599.6 2850.07   690.4 2863.28   719.8 2865.07   783.1  2876.5   855.2 2894.41
#Mann= 5 ,-1 , 0
       0      .1       0   179.4     .06       0   289.6      .1       0
   369.4    .045       0  397.66      .1       0
Bank Sta=369.4,397.66
XS Rating Curve= 0 ,0
Exp/Cntr(USF)=0,0
Exp/Cntr=0.3,0.1

Type RM Length L Ch R = 1 ,6656    ,112.5,113.2,112.2
XS GIS Cut Line= 3
 2083936.2114096418031.1911720482084170.14040369417822.177482456
2084539.72102937417440.139204547
#Sta/Elev= 30
       0 2930.78    30.1 2918.01    43.3 2909.83    56.5 2907.07      72 2896.46
      86  2890.3   106.9 2878.24   140.1 2874.53   162.1 2868.83   167.3 2866.53
   175.3 2858.23   195.2 2859.13   210.5 2857.68   227.2 2849.12   263.3 2839.49
   316.3 2837.42  358.442822.013   371.7 2820.69   382.4 2821.99   405.9 2829.93
     439 2834.38   452.7 2837.94   485.4  2838.8   493.7 2842.11   509.8 2843.69
   608.8 2848.68   667.2 2857.66   722.1 2863.48   814.8 2885.49   845.3 2895.52
#Mann= 7 ,-1 , 0
       0      .1       0  153.18     .06       0  268.25      .1       0
  358.44    .045       0   382.4      .1       0  749.76      .1       0
  842.05      .1       0
Bank Sta=358.44,382.4
XS Rating Curve= 0 ,0
Exp/Cntr=0.3,0.1

Type RM Length L Ch R = 1 ,6543    ,105.7,105.8,105.7
XS GIS Cut Line= 2
2084030.33654943 418136.390108632084608.93086469 417514.88577421
#Sta/Elev= 30
       0 2889.62     9.9 2888.01      20  2882.9    26.4 2880.96    50.3 2880.71
    68.2 2877.84   142.5 2857.01     150 2851.38   153.4 2850.03   171.3 2850.85
   186.6 2849.57   202.8 2840.52   236.7 2831.25   294.5 2829.71   323.4 2820.12
   341.6 2810.97   349.1 2805.91   360.7 2802.28   372.3 2799.85   377.5 2800.02
  384.942802.336   399.9 2809.59   418.7 2823.55   441.9 2829.91   543.3 2834.19
   621.9 2840.38     670 2849.29   691.3 2851.86   756.7 2864.58   849.1 2890.88
#Mann= 5 ,-1 , 0
       0      .1       0  111.16     .06       0  261.95      .1       0
   360.7    .045       0  384.94      .1       0
Bank Sta=360.7,384.94
XS Rating Curve= 0 ,0
Exp/Cntr=0.3,0.1

Type RM Length L Ch R = 1 ,6437    ,125.4,127,129.1
XS GIS Cut Line= 3
2084095.39383402418184.836862132 2084287.7973206418014.580640957
2084664.29853612417607.627058551
#Sta/Elev= 30
       0 2890.51    14.7 2884.41    36.5 2877.12    63.5  2869.7     110 2854.07
   123.9 2847.15   141.6 2847.51   154.1 2846.58   167.9 2838.65   181.1 2834.83
   242.4 2824.01   251.7 2817.92   277.3 2804.16   293.1 2800.98   318.2 2799.68
   344.6 2794.67   356.9 2793.48   367.8 2795.09   374.8 2799.35     398 2818.57
     405 2823.07   428.2 2820.98   449.5 2820.36   516.4 2826.51   561.2 2827.29
   598.4 2833.73   641.9 2837.71   675.7 2844.64   704.3 2848.66   811.3 2874.53
#Mann= 6 ,-1 , 0
       0    .055       0   30.37      .1       0   65.32     .06       0
  238.08      .1       0   344.6    .045       0   367.8      .1       0
Bank Sta=344.6,367.8
XS Rating Curve= 0 ,0
Exp/Cntr=0.3,0.1

Type RM Length L Ch R = 1 ,6310    ,309.2,309.7,310.1
XS GIS Cut Line= 4
2084134.15130243418241.5890452122084362.54389027418092.095577791
 2084433.1379092 418035.343722792084726.58745351417669.915647879
#Sta/Elev= 30
       0 2889.55     104 2856.27     118 2844.63   151.2 2843.29   165.4 2835.76
   190.2 2827.32   243.6 2815.21   253.1 2810.77   264.9 2809.19   285.2 2801.11
     302 2791.63  318.68 2786.76   327.3 2785.64   342.1 2787.09   355.2 2797.05
   365.6 2798.45   370.1 2802.09   377.1 2811.38   381.3 2812.67     418 2813.99
   454.6 2810.27   486.8 2815.16   524.1 2817.77   558.8 2816.19   577.7 2818.42
   613.5 2818.58   647.2 2827.58   748.2 2843.68   798.7 2859.26   832.2 2867.74
#Mann= 5 ,-1 , 0
       0    .055       0  146.87     .06       0  243.26      .1       0
  318.68    .045       0   342.1      .1       0
Bank Sta=318.68,342.1
XS Rating Curve= 0 ,0
Exp/Cntr=0.3,0.1

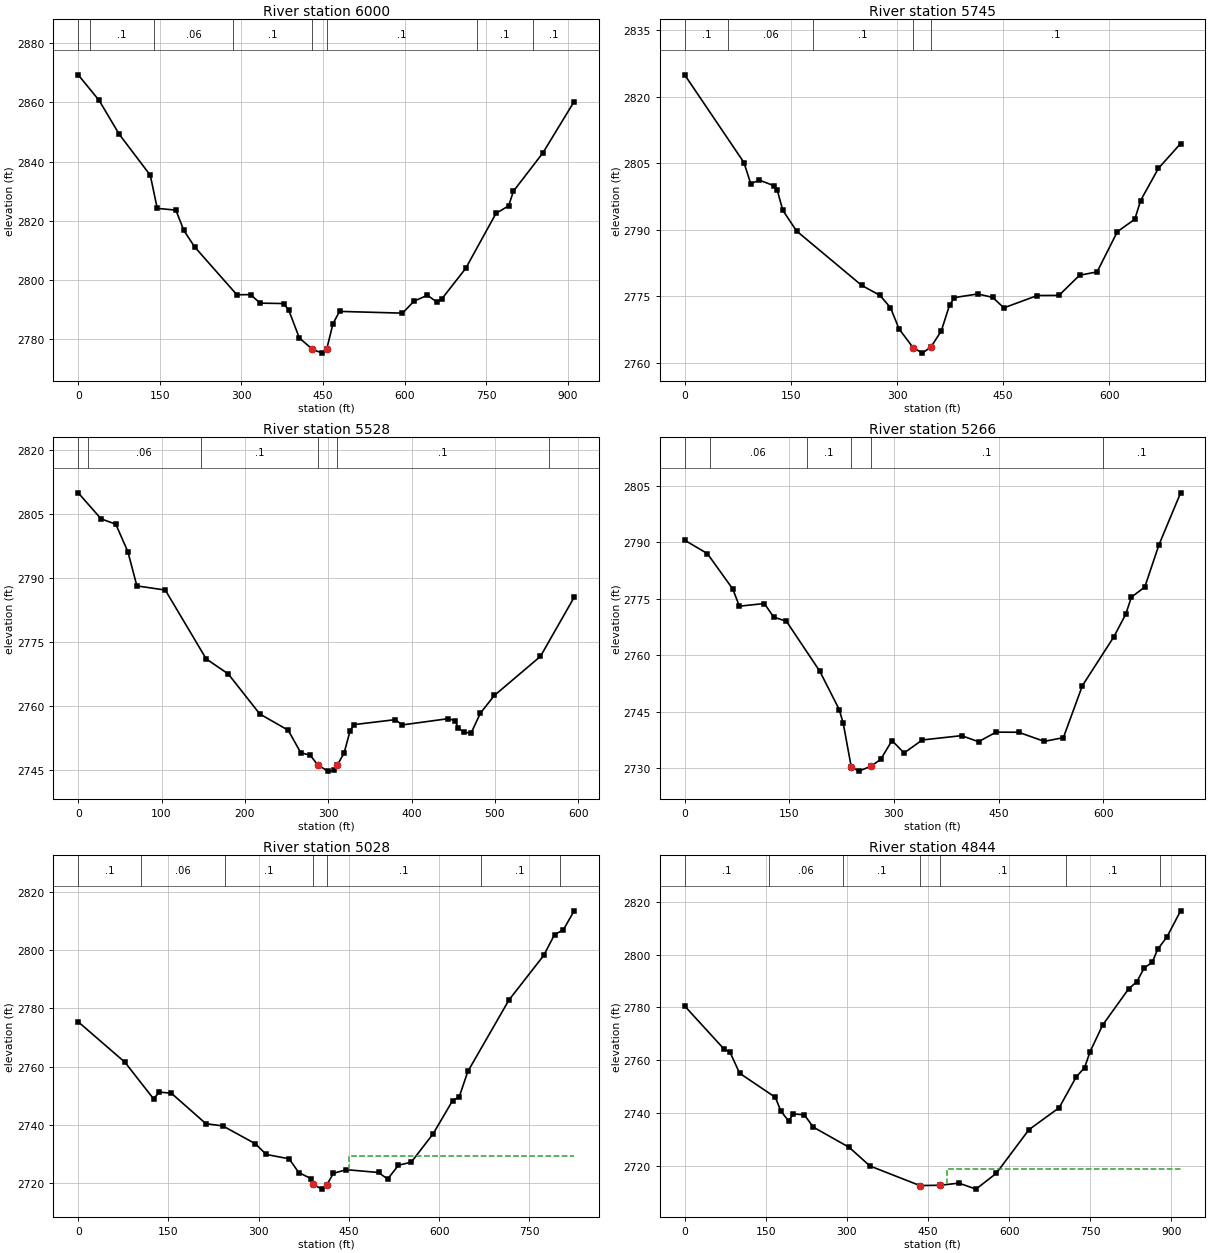
Type RM Length L Ch R = 1 ,6000    ,255.3,255.3,249.9
XS GIS Cut Line= 2
2084296.10242212418514.275835797 2084977.1269787 417907.99752079
#Sta/Elev= 30
       0 2869.35    38.5 2860.68    75.4 2849.24   132.5 2835.39   145.3 2824.18
   179.6 2823.59   194.1 2816.75   214.1 2811.13   291.7 2794.96   316.9 2795.01
   334.5 2792.13   377.7 2791.99   387.2  2789.7   406.5 2780.37   430.7 2776.48
   448.7 2775.22   456.7 2776.45   468.4 2785.17   480.5 2789.34   596.2 2788.74
   617.1 2792.76     642  2794.8   658.9 2792.55   668.2 2793.49   712.4 2803.88
   768.1 2822.49   791.4 2825.04   800.1 2829.99   854.1 2842.89   911.8  2860.3
#Mann= 8 ,-1 , 0
       0    .055       0   21.33      .1       0  139.05     .06       0
  284.27      .1       0   430.7    .045       0   456.7      .1       0
  732.34      .1       0  836.92      .1       0
Bank Sta=430.7,456.7
XS Rating Curve= 0 ,0
Exp/Cntr=0.3,0.1

Type RM Length L Ch R = 1 ,5745    ,217.8,217,214.3
XS GIS Cut Line= 2
 2084568.7892127418685.9159124642084990.96914262418126.700495467
#Sta/Elev= 30
       0 2824.89    83.7 2805.14    93.3 2800.38   105.7 2801.16   126.2 2799.91
   130.6 2799.02   138.6 2794.38   158.1 2789.71     250 2777.47   275.8 2775.23
   290.7 2772.46     303 2767.62   322.7 2763.45   335.9  2762.2   348.2 2763.64
   362.5 2767.18   374.2    2773   381.2 2774.71     414 2775.53   435.1 2774.76
     451  2772.4   498.3 2775.18   528.8  2775.2   557.9 2779.74   582.7  2780.5
   611.3 2789.55     636 2792.37   644.2 2796.58   669.3 2803.82   700.7  2809.4
#Mann= 5 ,-1 , 0
       0      .1       0   61.36     .06       0  181.62      .1       0
   322.7    .045       0   348.2      .1       0
Bank Sta=322.7,348.2
XS Rating Curve= 0 ,0
Exp/Cntr=0.3,0.1

Type RM Length L Ch R = 1 ,5528    ,261.1,262.2,264.5
XS GIS Cut Line= 2
2084801.33402318418793.8835442962085097.55226278418277.578146458
#Sta/Elev= 30
       0 2809.94    27.4 2803.84    45.1 2802.57    59.6 2796.12    70.4  2788.1
   104.5 2787.12   153.6 2770.97   180.1 2767.43   217.9 2758.04     252 2754.23
   267.1 2748.94   278.5 2748.34   287.9 2745.99   299.9 2744.63   307.1 2744.81
  310.872746.027   319.1 2748.87   326.3 2754.09   331.1 2755.55   380.6 2756.71
   388.8 2755.47   444.1 2756.94   452.4 2756.46   456.1 2754.71   462.5 2753.82
   471.4 2753.52   482.7 2758.24   499.4 2762.38   554.8 2771.57   595.2 2785.43
#Mann= 6 ,-1 , 0
       0      .1       0   11.25     .06       0  147.28      .1       0
   287.9    .045       0  310.87      .1       0  565.18      .1       0
Bank Sta=287.9,310.87
XS Rating Curve= 0 ,0
Exp/Cntr=0.3,0.1

Type RM Length L Ch R = 1 ,5266    ,242.5,237.3,233.8
XS GIS Cut Line= 3
2084962.24413443418915.1313332922085156.03147653418685.970046207
2085323.67320162418310.699143216
#Sta/Elev= 30
       0 2790.59    32.5 2787.04    69.1 2777.59    78.4 2773.07   114.2 2773.78
   127.6 2770.19   145.9 2769.06   193.7 2755.81   221.6 2745.63   227.4 2741.93
   238.8 2730.43   249.5 2729.28     267 2730.56     281 2732.39   297.3  2737.4
   314.5  2734.1   340.7 2737.55     397  2738.7   421.3 2737.09   446.5 2739.63
   478.8  2739.6   515.6 2737.18     543 2738.17   570.3 2751.99   615.3 2764.92
   632.4 2770.93   640.5 2775.47   659.7 2778.15     680 2789.35   711.1 2803.17
#Mann= 6 ,-1 , 0
       0      .1       0   35.68     .06       0  175.21      .1       0
   238.8    .045       0     267      .1       0  599.45      .1       0
Bank Sta=238.8,267
XS Rating Curve= 0 ,0
Exp/Cntr=0.3,0.1

Type RM Length L Ch R = 1 ,5028    ,185.7,184.5,182.8
XS GIS Cut Line= 2
 2085192.9434762419128.9130579682085534.37848887418378.370923877
#Sta/Elev= 30
       0 2775.37    77.6 2761.53   125.2    2749   135.1 2751.29   154.9 2750.89
   212.3 2740.46   240.5 2739.69   294.6 2733.57   312.6 2729.91   350.6 2728.43
   366.7 2723.72   386.6 2721.66  390.332719.659   405.1 2718.03   413.5 2719.55
   424.4 2723.47     446 2724.69   499.3 2723.73   514.5 2721.48   532.5 2726.22
   553.8 2727.27   590.2 2737.03   622.6 2748.38   633.4 2749.59   647.8 2758.35
   716.3 2782.88     774 2798.12     792 2805.27   806.5 2806.85   824.6 2813.41
#Mann= 7 ,-1 , 0
       0      .1       0  104.43     .06       0  244.02      .1       0
  390.33    .045       0   413.5      .1       0   669.3      .1       0
  800.55      .1       0
#XS Ineff= 2 , 0
                          451.05         2729.55
Permanent Ineff=
       F       F
Bank Sta=390.33,413.5
XS Rating Curve= 0 ,0
Exp/Cntr=0.3,0.1

Type RM Length L Ch R = 1 ,4844    ,102,100.4,99
XS GIS Cut Line= 3
2085369.68787336419260.6769020412085527.97200561418835.767974958
2085688.83388862418400.774094298
#Sta/Elev= 30
       0 2780.55    73.2 2764.17    83.7 2763.13   101.6 2755.14   167.7 2746.02
   177.9 2740.81   192.2  2737.1   201.1 2739.79   221.5 2739.37   237.7 2734.78
   304.2 2727.12   342.7 2720.06     435 2712.67   472.3 2712.78   507.2 2713.59
   538.7 2711.32   576.2 2717.28   636.7  2733.8   692.6  2742.1   724.1 2753.73
   739.6 2757.26   749.8  2763.3   773.1 2773.38   821.3 2787.09   836.1 2789.69
     850 2794.98   864.7 2797.03   874.5 2801.91     892 2806.68   917.2 2816.53
#Mann= 7 ,-1 , 0
       0      .1       0  155.75     .06       0  293.64      .1       0
     435    .045       0   472.3      .1       0   704.3      .1       0
  878.94      .1       0
#XS Ineff= 2 , 0
                             485         2718.84
Permanent Ineff=
       F       F
Bank Sta=435,472.3
XS Rating Curve= 0 ,0
Exp/Cntr=0.3,0.1