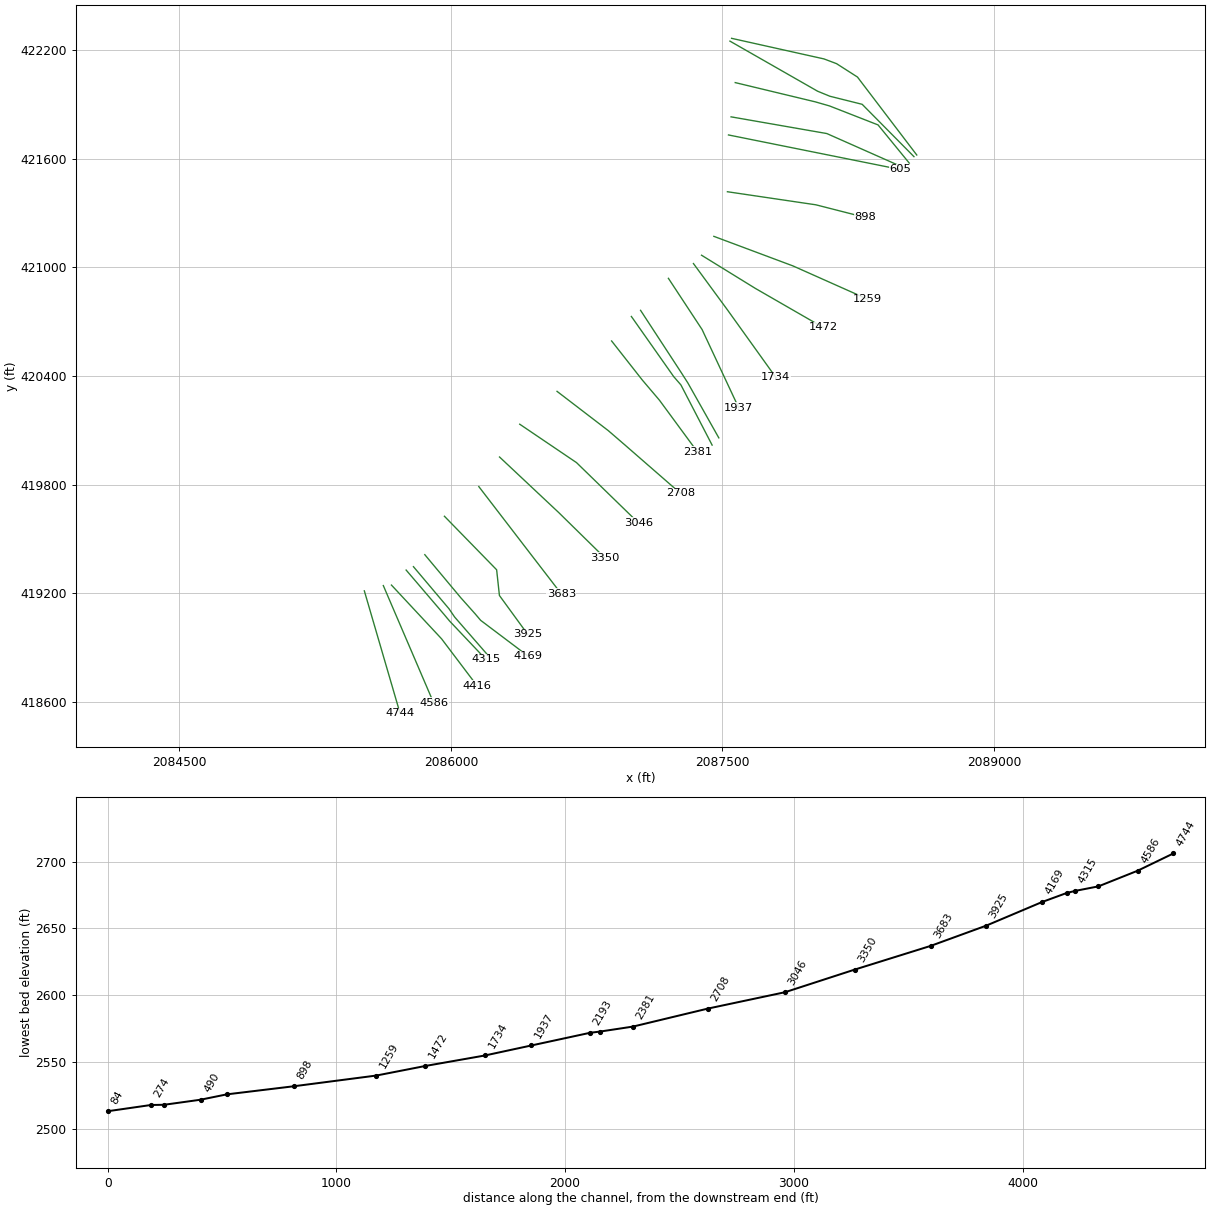
HEC-RAS study MCMILLCK.prj: MCMILLCK

--- MCMILLCK.g01 (geometry) --- (continued)

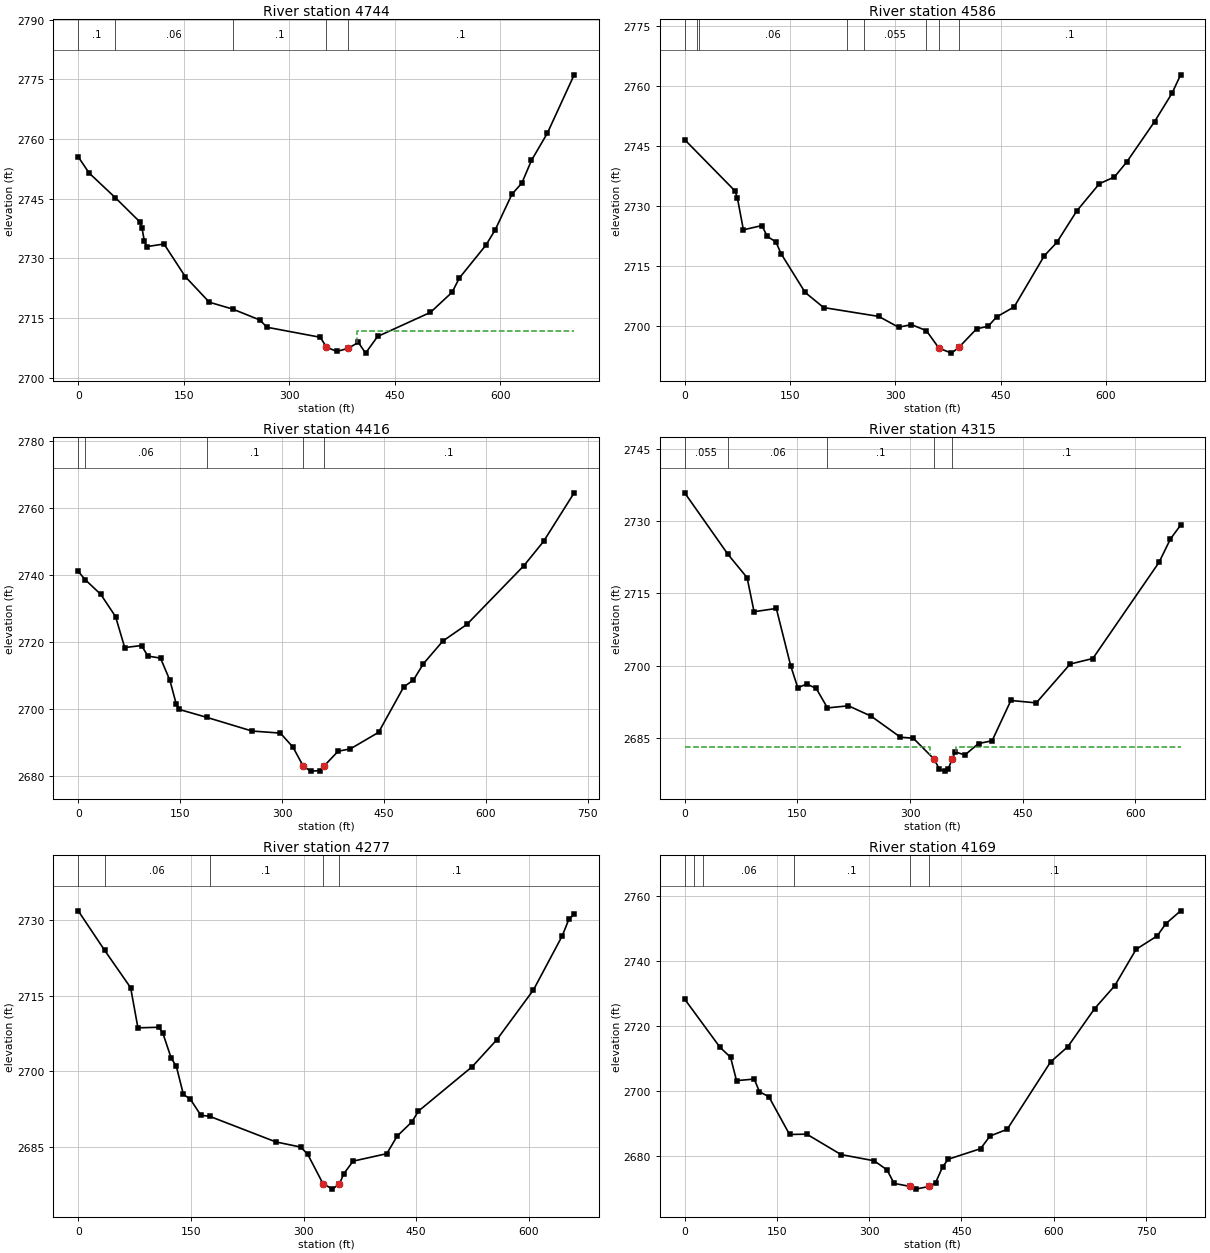
Type RM Length L Ch R = 1 ,4744    ,154.3,157.1,157.8
XS GIS Cut Line= 2
2085521.78340813419213.575094077 2085719.3397144418536.720249304
#Sta/Elev= 30
       0  2755.5    15.5 2751.43      53 2745.19    87.3 2739.21    90.7 2737.59
    94.1 2734.28    97.5 2732.94     122  2733.6   152.2  2725.4   186.4 2718.97
   219.9 2717.23   258.2 2714.51   268.4 2712.68   344.2 2710.16   352.82707.715
   367.5  2706.6   383.22707.348   398.3 2708.86   408.6 2706.18   425.6 2710.36
   500.8 2716.42   531.6 2721.48   541.8 2725.03   579.7 2733.32   592.9 2737.16
   616.7 2746.12   630.7 2748.89   644.4  2754.6     667 2761.44   705.1  2776.1
#Mann= 5 ,-1 , 0
       0      .1       0      53     .06       0   219.9      .1       0
   352.8    .045       0   383.2      .1       0
#XS Ineff= 2 , 0
                           396.6         2711.76
Permanent Ineff=
       F       F
Bank Sta=352.8,383.2
XS Rating Curve= 0 ,0
Exp/Cntr(USF)=0,0
Exp/Cntr=0.3,0.1

Type RM Length L Ch R = 1 ,4586    ,164.2,170.7,174
XS GIS Cut Line= 2
2085626.65815994419242.7245101332085905.03555593418593.690375134
#Sta/Elev= 30
       0 2746.64    71.6 2733.81      75  2732.1    83.6 2724.06     110 2725.13
   117.5 2722.44     130    2721   137.2  2718.1   171.5 2708.39   197.9 2704.59
   276.4 2702.37   304.6 2699.66   322.8 2700.33   344.2  2698.8   362.1 2694.42
   379.9 2693.18   390.6 2694.65   415.6 2699.25   432.3 2699.93   444.2 2702.25
   469.2 2704.76     512 2717.54   529.9  2720.9   558.4 2728.81   590.5 2735.61
     612  2737.3   629.6 2741.08   669.1 2751.16   694.1 2758.32   706.2 2762.88
#Mann= 8 ,-1 , 0
       0    .055       0   17.35      .1       0   20.67     .06       0
  230.43      .1       0  255.97    .055       0   344.2      .1       0
   362.1    .045       0   390.6      .1       0
Bank Sta=362.1,390.6
XS Rating Curve= 0 ,0
Exp/Cntr=0.3,0.1

Type RM Length L Ch R = 1 ,4416    ,101.6,101,100.9
XS GIS Cut Line= 3
2085671.61377868419245.4597408772085948.45312002418948.626345038
2086143.77851677418690.243003547
#Sta/Elev= 30
       0  2741.2    10.1 2738.75    33.2 2734.32      55 2727.67    68.4 2718.43
    93.2 2719.04   102.5 2715.89   121.1 2715.28     135  2708.6   144.3 2701.49
   148.6 2699.95   189.6 2697.56   255.7  2693.5   297.5 2692.88   316.1 2688.67
   331.22682.976   342.1 2681.52   355.6 2681.66   361.82683.051   382.5 2687.47
   400.4 2688.16     442  2693.1     479 2706.67   493.3 2708.74   507.8 2713.56
   536.6 2720.38   571.9 2725.34   655.9 2742.91   684.7 2750.12   729.8 2764.66
#Mann= 5 ,-1 , 0
       0    .055       0    10.1     .06       0   189.6      .1       0
   331.2    .045       0   361.8      .1       0
Bank Sta=331.2,361.8
XS Rating Curve= 0 ,0
Exp/Cntr=0.5,0.3

Type RM Length L Ch R = 1 ,4315    ,39.3,38.1,37
XS GIS Cut Line= 4
2085752.77306518 419328.404128792085961.10630995419084.653960124
2085993.05079985419046.4598107932086192.35617551418836.042908788
#Sta/Elev= 30
       0 2735.84    57.5 2723.11    83.1 2718.25    92.4 2711.19     122 2711.87
   141.2 2699.95   150.6 2695.43   162.4 2696.19     175 2695.32   190.1 2691.25
   218.1 2691.68   248.3 2689.53   287.2 2685.18   304.4 2684.96   332.1 2680.63
   339.1 2678.54     346 2678.14   350.7 2678.49   355.9 2680.57   360.2 2682.11
   373.2  2681.5   391.2 2683.86   409.3 2684.43   434.3 2692.79   468.1 2692.29
   513.2 2700.34   543.4 2701.49   631.6 2721.44   646.8 2726.29   660.3 2729.14
#Mann= 5 ,-1 , 0
       0    .055       0    57.5     .06       0   190.1      .1       0
   332.1    .045       0   355.9      .1       0
#XS Ineff= 2 , 0
           326.1  2683.1   361.9          2683.1
Permanent Ineff=
       F       F
Bank Sta=332.1,355.9
XS Rating Curve= 0 ,0
Exp/Cntr=0.5,0.3

Type RM Length L Ch R = 1 ,4277    ,100.3,108,107.4
XS GIS Cut Line= 4
2085793.05087176419347.1540912992085989.57836586419114.515120879
2086020.82863143419068.6818792072086218.05067796418842.292896301
#Sta/Elev= 30
       0 2731.83      35 2724.02    69.8 2716.56    79.5 2708.59   107.4  2708.7
   112.8 2707.48   123.7 2702.61   130.7 2700.92     140 2695.37   149.3 2694.41
   163.3 2691.22   174.9 2691.02   263.1 2685.93     296 2684.91   305.3 2683.54
   325.8 2677.66   338.4 2676.55   347.8 2677.59   353.6 2679.61     366 2682.11
   410.8 2683.59   424.7 2687.09   444.3 2689.91     453 2692.05   524.7 2700.89
   557.3 2706.22   606.1 2716.12   644.5 2726.87   653.2 2730.14   660.3 2731.16
#Mann= 5 ,-1 , 0
       0    .055       0      35     .06       0   174.9      .1       0
   325.8    .045       0   347.8      .1       0
Bank Sta=325.8,347.8
XS Rating Curve= 0 ,0
Exp/Cntr=0.5,0.3

Type RM Length L Ch R = 1 ,4169    ,242.6,243.8,226.7
XS GIS Cut Line= 5
 2085855.8197751419413.442344546  2086053.319863419177.035155973
2086133.96864793419086.5336907242086164.24608848419050.760223199
2086427.95445761418852.073716626
#Sta/Elev= 30
       0 2728.26    57.5 2713.41    74.6 2710.36    84.3 2703.16   113.1 2703.65
   121.5 2699.77   136.9 2698.19   170.5 2686.58   198.5 2686.68   254.2 2680.39
     308 2678.48   328.9 2675.69   340.5 2671.51   366.9 2670.57   375.3 2669.75
   397.7 2670.58   407.9 2671.72   419.5 2676.66   428.5 2678.96   481.1 2682.21
   496.4  2686.1   524.4 2688.18   594.8 2708.89     623 2713.64   666.5 2725.35
   699.2 2732.39   733.9  2743.6   768.2 2747.73   782.2 2751.48   806.3 2755.46
#Mann= 6 ,-1 , 0
       0    .055       0   15.33      .1       0   29.65     .06       0
  177.64      .1       0   366.9    .045       0   397.7      .1       0
Bank Sta=366.9,397.7
XS Rating Curve= 0 ,0
Exp/Cntr=0.3,0.1

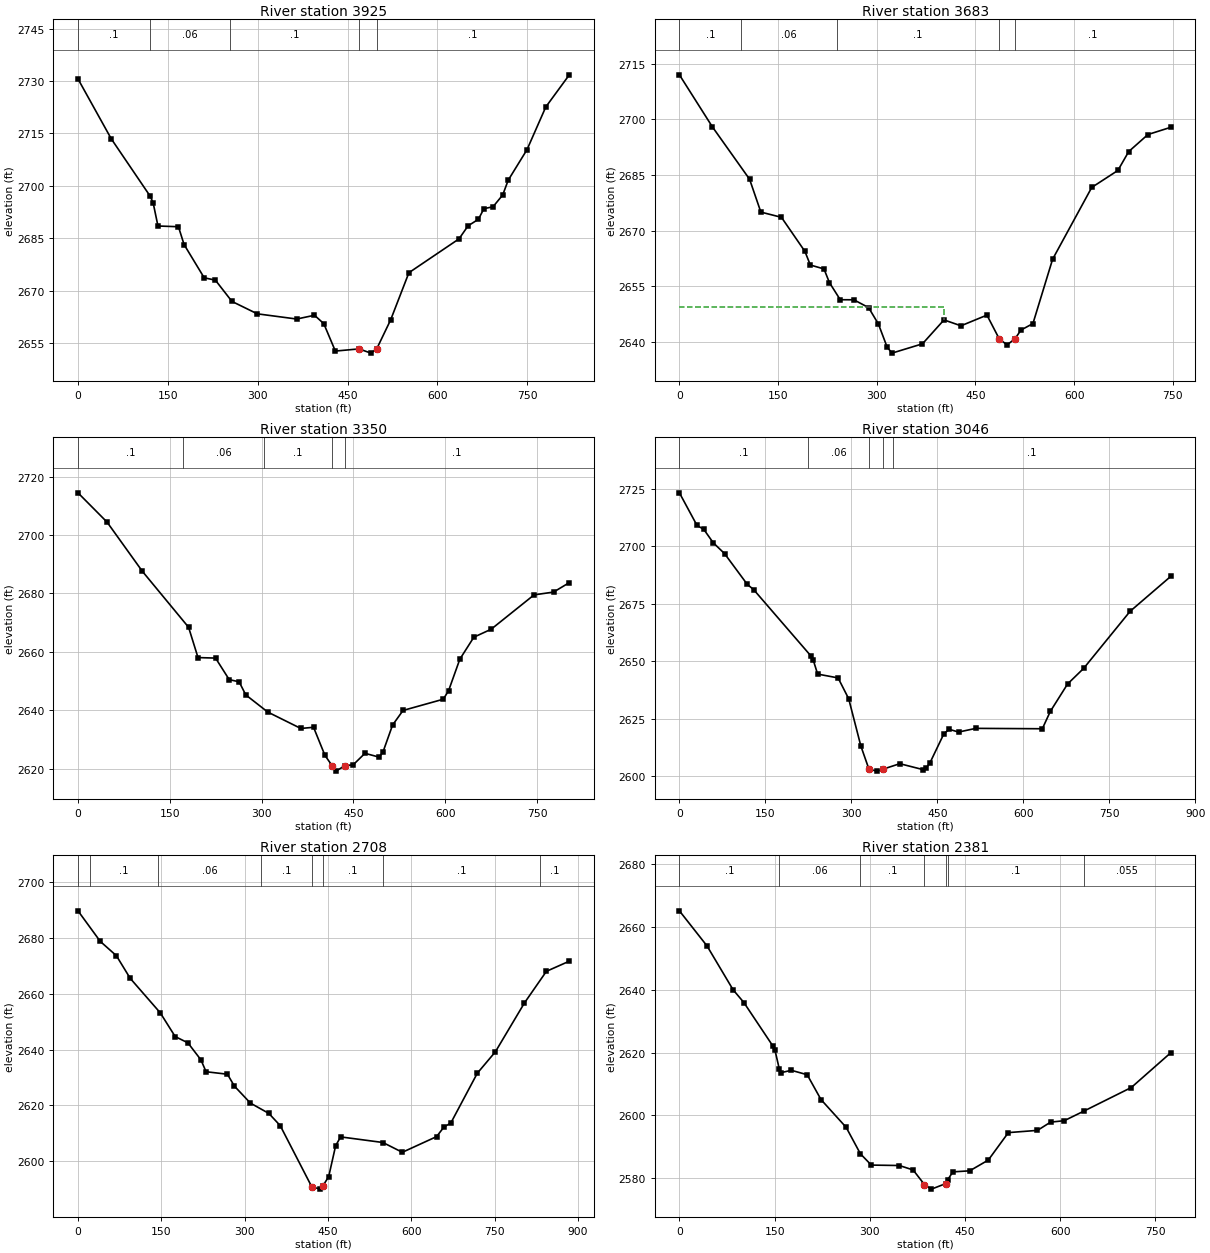
Type RM Length L Ch R = 1 ,3925    ,239.8,242.2,253.3
XS GIS Cut Line= 4
2085964.24306957419625.6214867272086252.64496979419330.031230909
2086268.10150579419187.8468143462086423.66998795418974.320001402
#Sta/Elev= 30
       0 2730.59    55.6 2713.43   120.8 2696.95   125.5 2695.09   133.5 2688.49
   167.7 2688.28   177.1 2683.18   210.7 2673.66   229.3    2673     257  2666.9
   299.3 2663.35   365.1 2661.86   394.8 2662.94   410.3 2660.54   429.6 2652.69
   469.2 2653.31     489  2652.1   498.8 2653.37     522 2661.65   552.4 2675.12
     636  2684.8   651.2 2688.54   668.4 2690.41   677.6 2693.45   692.8 2693.99
     709 2697.37   718.1 2701.58   749.6 2710.36   780.9 2722.56   820.2 2731.76
#Mann= 5 ,-1 , 0
       0      .1       0   120.7     .06       0   253.5      .1       0
   469.2    .045       0   498.8      .1       0
Bank Sta=469.2,498.8
XS Rating Curve= 0 ,0
Exp/Cntr(USF)=0,0
Exp/Cntr=0.3,0.1

Type RM Length L Ch R = 1 ,3683    ,328.6,332.7,331.5
XS GIS Cut Line= 3
2086154.19647494419789.5833245522086429.49776161419431.230366707
2086609.44326785419197.454915628
#Sta/Elev= 30
       0 2712.02    50.1    2698   106.7 2683.86   123.8 2675.01   155.1  2673.6
   190.8 2664.41     199 2660.74   219.8 2659.68     228 2656.01   244.5 2651.38
   265.2 2651.36   287.6 2649.25   302.5 2644.83   315.7 2638.63   323.1 2636.98
   369.5 2639.49   402.2 2645.94     428 2644.35   467.5 2647.23   486.5 2640.72
   498.2 2639.23   509.9 2640.79   519.2  2643.2   537.4 2644.95   567.3  2662.3
   626.8 2681.66   666.5 2686.23     683 2691.33   712.2 2695.92   746.9 2697.87
#Mann= 5 ,-1 , 0
       0      .1       0   94.16     .06       0   239.4      .1       0
   486.5    .045       0   509.9      .1       0
#XS Ineff= 2 , 0
          402.86  2649.3
Permanent Ineff=
       F       F
Bank Sta=486.5,509.9
XS Rating Curve= 0 ,0
Exp/Cntr=0.3,0.1

Type RM Length L Ch R = 1 ,3350    ,304.6,304.4,305.4
XS GIS Cut Line= 3
2086268.64736152419953.0029452152086594.70248368419646.941877544
2086848.47198927419397.786207885
#Sta/Elev= 30
       0 2714.43    47.5 2704.41   105.1  2687.6   180.7 2668.43   196.1 2658.06
   224.8 2657.89   247.1 2650.51   263.3 2649.78   274.1  2645.3   310.1 2639.42
   364.1 2633.81   384.9 2634.21   403.5  2624.6  415.052621.126   421.5 2619.21
  436.262621.089   449.7 2621.38   468.9 2625.31   492.3 2623.98   498.6 2625.92
     514 2634.98   531.1 2639.97   596.8 2643.81   605.4 2646.67   623.9 2657.51
   646.8 2665.04     675 2667.75   745.2 2679.52     777 2680.47   802.8 2683.71
#Mann= 5 ,-1 , 0
       0      .1       0  171.99     .06       0  303.78      .1       0
  415.05    .045       0  436.26      .1       0
Bank Sta=415.05,436.26
XS Rating Curve= 0 ,0
Exp/Cntr=0.3,0.1

Type RM Length L Ch R = 1 ,3046    ,333,338.3,328.8
XS GIS Cut Line= 3
2086380.28198078 420134.09444654 2086694.0329937419921.851104632
2087037.00638911419588.105709121
#Sta/Elev= 30
       0 2723.27    30.7 2709.11    42.6 2707.37      59 2701.58    78.8 2696.84
   118.4 2683.49   129.5 2681.21   229.3 2652.42   233.3 2650.77   241.2 2644.48
   276.9 2642.81   295.4 2633.75   316.6 2613.24   330.8  2603.1     345 2602.29
  354.572603.089   384.6 2605.52   424.5 2602.99   430.4 2603.58   437.2 2605.89
   461.6 2618.57   470.9 2620.47   487.1 2619.27   517.3 2620.88   633.3 2620.71
   647.2 2628.23   677.4 2640.18   705.4 2646.95   786.4 2671.75   857.4 2686.95
#Mann= 5 ,-1 , 0
       0      .1       0  224.05     .06       0   330.8    .045       0
  354.57     .06       0  372.85      .1       0
Bank Sta=330.8,354.57
XS Rating Curve= 0 ,0
Exp/Cntr=0.3,0.1

Type RM Length L Ch R = 1 ,2708    ,326.7,326.1,322.7
XS GIS Cut Line= 4
 2086586.3734321 420315.578007462086869.36466402420098.720501542
2086958.56855386420021.8207209562087267.70573086419752.671324879
#Sta/Elev= 30
       0 2689.79    40.1 2678.83    69.1  2673.7      94 2665.57     148 2653.23
   174.9  2644.7   197.8 2642.45   221.2 2636.36   230.5 2632.09     269 2631.19
   281.4 2626.95   310.3 2620.84   343.4 2617.15   363.9 2612.77  420.672590.832
     436 2589.99   440.6 2591.14   451.1 2594.44   463.7 2605.59   472.7 2608.72
   548.7 2606.71   583.7  2603.2   645.3 2608.82   658.6 2612.27   670.9 2613.69
   718.6 2631.56   751.1 2639.23   803.5 2656.78   842.9 2668.09   884.2 2671.74
#Mann= 8 ,-1 , 0
       0    .055       0    21.7      .1       0  144.63     .06       0
  330.13      .1       0  420.67    .045       0   440.6      .1       0
  549.52      .1       0  831.23      .1       0
Bank Sta=420.67,440.6
XS Rating Curve= 0 ,0
Exp/Cntr=0.3,0.1

Type RM Length L Ch R = 1 ,2381    ,145.4,146.1,145.4
XS GIS Cut Line= 4
2086887.82066387420593.9554034622087057.00011551420378.635952204
2087152.35589594420266.362226635 2087361.5234566419981.832940042
#Sta/Elev= 30
       0  2665.1    43.5 2653.94    84.6 2639.99   101.6 2635.93   147.2 2622.13
   150.7 2620.68   157.4 2614.82   160.4 2613.63   176.4 2614.37   201.4 2612.96
   223.1 2605.07   262.8 2596.22   285.2 2587.82   302.4 2584.22   346.6 2584.08
   368.3 2582.67   386.2 2578.01   397.2 2576.57  419.872578.338   422.9  2579.6
     431 2582.06   457.5 2582.39   486.8 2585.82   518.4 2594.55   564.3 2595.26
   584.9 2597.88   606.5 2598.34     637 2601.35   712.1 2608.89   774.3 2619.95
#Mann= 7 ,-1 , 0
       0      .1       0   157.4     .06       0   285.2      .1       0
   386.2    .045       0  419.87      .1       0   422.9      .1       0
     637    .055       0
Bank Sta=386.2,419.87
XS Rating Curve= 0 ,0
Exp/Cntr=0.5,0.3

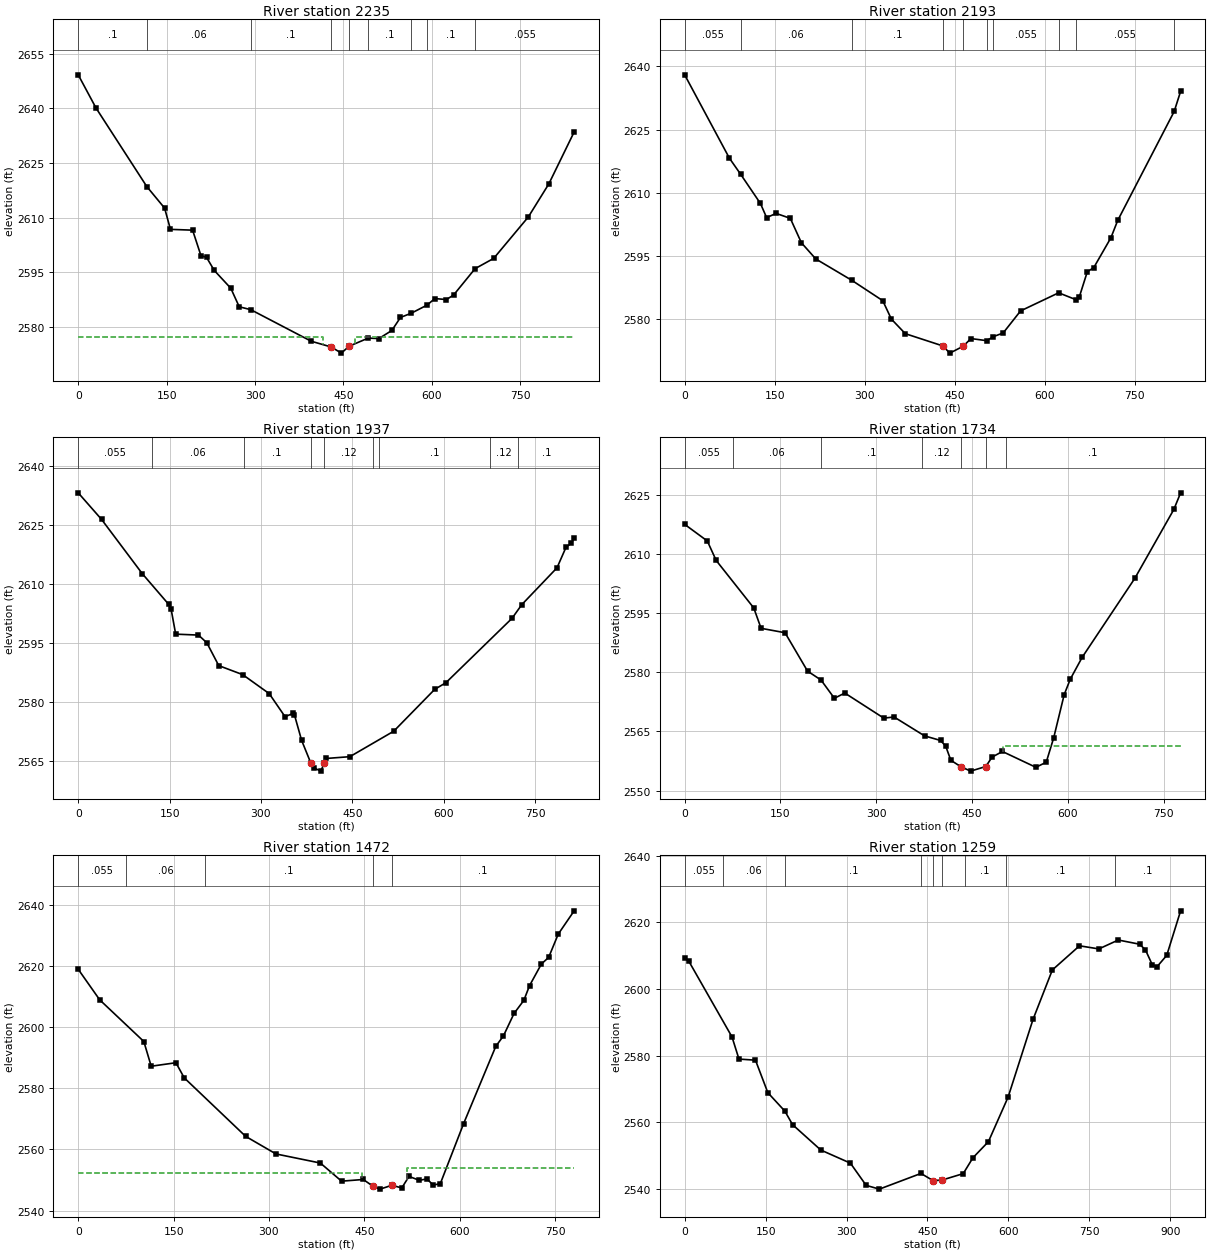
Type RM Length L Ch R = 1 ,2235    ,43.9,41.9,39.7
XS GIS Cut Line= 4
2086997.01828012420729.2989647982087230.79373118420397.091952041
2087270.78184021420350.951952457 2087443.0374012420018.744611621
#Sta/Elev= 30
       0 2649.21    30.2  2640.1   116.4 2618.52   146.6  2612.6   156.5 2606.77
   194.1 2606.55   208.3 2599.54   217.7 2599.09   230.8  2595.5   258.9  2590.6
   273.2 2585.51   292.7 2584.72   395.3 2576.05  429.442574.457   446.5 2572.78
  459.542574.674     492  2576.9   510.3 2576.79   532.2 2579.01   546.8 2582.58
   565.1 2583.74   591.8 2585.96   605.2 2587.77   624.7 2587.49   636.9 2588.73
   673.4 2595.98     705  2598.8   763.7 2610.17   798.5 2619.25   841.5 2633.52
#Mann= 9 ,-1 , 0
       0      .1       0   116.4     .06       0   292.7      .1       0
  429.44    .045       0  459.54      .1       0     492      .1       0
   565.1    .055       0   591.8      .1       0   673.4    .055       0
#XS Ineff= 2 , 0
          414.95  2577.2   469.5          2577.2
Permanent Ineff=
       F       F
Bank Sta=429.44,459.54
XS Rating Curve= 0 ,0
Exp/Cntr=0.5,0.3

Type RM Length L Ch R = 1 ,2193    ,257.3,256.9,260.6
XS GIS Cut Line= 4
2087047.77211562420763.1348551212087273.85762143420417.085678458
2087309.23156643420361.7180070432087479.94907278420058.732720628
#Sta/Elev= 30
       0 2638.02    74.6 2618.21    93.1 2614.44   126.3 2607.46   136.6  2604.1
   152.4  2605.1   176.1 2603.93   194.6 2598.12   218.6 2594.28   278.6 2589.21
   330.2 2584.37   344.6 2579.99   367.8 2576.53   430.4 2573.62     442 2571.91
  464.182573.534   477.3 2575.37   503.5 2574.87   514.8 2575.84   530.9 2576.69
     560 2581.94   623.5 2586.24   653.1 2584.56   657.9 2585.25   671.2 2591.23
     682 2592.22   710.6 2599.32   721.9 2603.42   816.1 2629.33   826.8  2634.1
#Mann= 10 ,-1 , 0
       0    .055       0    93.1     .06       0   278.6      .1       0
   430.4    .045       0  464.18      .1       0   503.5      .1       0
   514.8    .055       0   623.5      .1       0   653.1    .055       0
   816.1      .1       0
Bank Sta=430.4,464.18
XS Rating Curve= 0 ,0
Exp/Cntr=0.5,0.3

Type RM Length L Ch R = 1 ,1937    ,197.4,202.7,208.3
XS GIS Cut Line= 3
2087201.57200485420940.0045801252087387.66940168420657.013020128
2087589.14701712420226.374117628
#Sta/Elev= 30
       0 2633.13    38.3 2626.38     105 2612.62   148.3 2604.83   152.4 2603.65
     160 2597.22   197.4 2596.98   211.1 2595.03   230.7 2589.22     270 2586.93
   313.5 2582.11   339.5 2576.25     353 2577.09     355 2576.68   366.7 2570.24
   381.5 2564.59   387.6 2563.17   398.5 2562.41   403.7 2564.54   407.2 2565.63
   445.9 2566.08     518 2572.56   585.2 2583.19   603.6 2584.88   712.2 2601.25
   728.1 2604.71     786 2614.09     801 2619.39   809.7 2620.33   814.1 2621.71
#Mann= 9 ,-1 , 0
       0    .055       0  121.47     .06       0  271.84      .1       0
   381.5    .045       0   403.7     .12       0     484      .1       0
  494.55      .1       0  676.08     .12       0  722.64      .1       0
Bank Sta=381.5,403.7
XS Rating Curve= 0 ,0
Exp/Cntr=0.3,0.1

Type RM Length L Ch R = 1 ,1734    ,254.4,262.3,267.9
XS GIS Cut Line= 3
2087339.99134743421021.5181966282087530.70290828420761.596800461
2087795.23846844420392.477788046
#Sta/Elev= 30
       0 2617.53    35.4 2613.32    49.3 2608.38   108.2 2596.32   119.6 2591.16
   157.1 2590.04   192.4  2580.3   213.5 2578.04   234.4 2573.41   250.7 2574.74
   311.7 2568.38   327.9 2568.66   375.6 2563.87   400.6 2562.71   408.7 2561.26
   416.7 2557.69     432 2556.09   447.7 2554.93  471.482556.103   481.3 2558.49
   497.5 2559.91   549.9  2555.9   566.1 2557.19   577.8  2563.4   594.2 2574.33
   603.7 2578.24   622.3 2583.79   704.8 2603.84   765.9 2621.32   776.5 2625.53
#Mann= 7 ,-1 , 0
       0    .055       0   75.32     .06       0  212.98      .1       0
  372.01     .12       0     432    .045       0  471.48     .12       0
  502.44      .1       0
#XS Ineff= 2 , 0
                          498.02         2561.36
Permanent Ineff=
       F       F
Bank Sta=432,471.48
XS Rating Curve= 0 ,0
Exp/Cntr=0.3,0.1

Type RM Length L Ch R = 1 ,1472    ,211,212.4,213.6
XS GIS Cut Line= 3
2087384.59329236421067.6581962112087681.42668819420884.636580631
 2088055.1598646420669.317129374
#Sta/Elev= 30
       0 2618.88    33.8 2608.89   103.2 2595.27   114.8 2587.19   153.7 2588.33
   166.7  2583.4   263.3 2564.27     311 2558.52   380.8 2555.55   414.2 2549.62
   448.3 2550.17  462.982548.058   474.8 2547.02  493.142548.268   508.9 2547.42
   520.3 2551.18   536.5  2549.9   548.6 2550.36   558.2 2548.34   569.5 2548.81
   606.2 2568.46   656.8 2593.71   668.7 2597.07   685.5 2604.45   700.9 2608.73
   709.8 2613.51   728.5 2620.61   739.9 2622.76     755 2630.38     780 2637.98
#Mann= 5 ,-1 , 0
       0    .055       0   75.22     .06       0  199.46      .1       0
  462.98    .045       0  493.14      .1       0
#XS Ineff= 2 , 0
          445.95 2552.19  516.58         2554.07
Permanent Ineff=
       F       F
Bank Sta=462.98,493.14
XS Rating Curve= 0 ,0
Exp/Cntr=0.3,0.1

Type RM Length L Ch R = 1 ,1259    ,359,360.7,363.6
XS GIS Cut Line= 3
2087452.68994093421171.8699300442087889.27797851 421008.67603071
2088303.07505119420824.250874624
#Sta/Elev= 30
       0 2609.14     7.1 2608.47    87.7 2585.59   100.6 2578.94   131.2 2578.61
   154.1 2568.86   185.7 2563.31     200 2559.25   252.3 2551.64   307.1 2547.71
   336.3 2541.04   360.8 2539.91   437.9 2544.62  460.112542.486   476.7 2542.62
   516.2 2544.56   534.2 2549.32   562.9 2554.16   599.4 2567.53   645.5 2590.82
   681.4 2605.69   731.7 2612.93   767.6    2612   803.6 2614.67   843.1 2613.41
   853.9 2611.72   866.5 2607.27   875.4 2606.66   893.4 2610.07   919.1 2623.43
#Mann= 9 ,-1 , 0
       0    .055       0   70.33     .06       0  186.81      .1       0
   438.8      .1       0  460.11    .045       0   476.7      .1       0
  518.95      .1       0  595.01      .1       0  797.95      .1       0
Bank Sta=460.11,476.7
XS Rating Curve= 0 ,0
Exp/Cntr=0.3,0.1

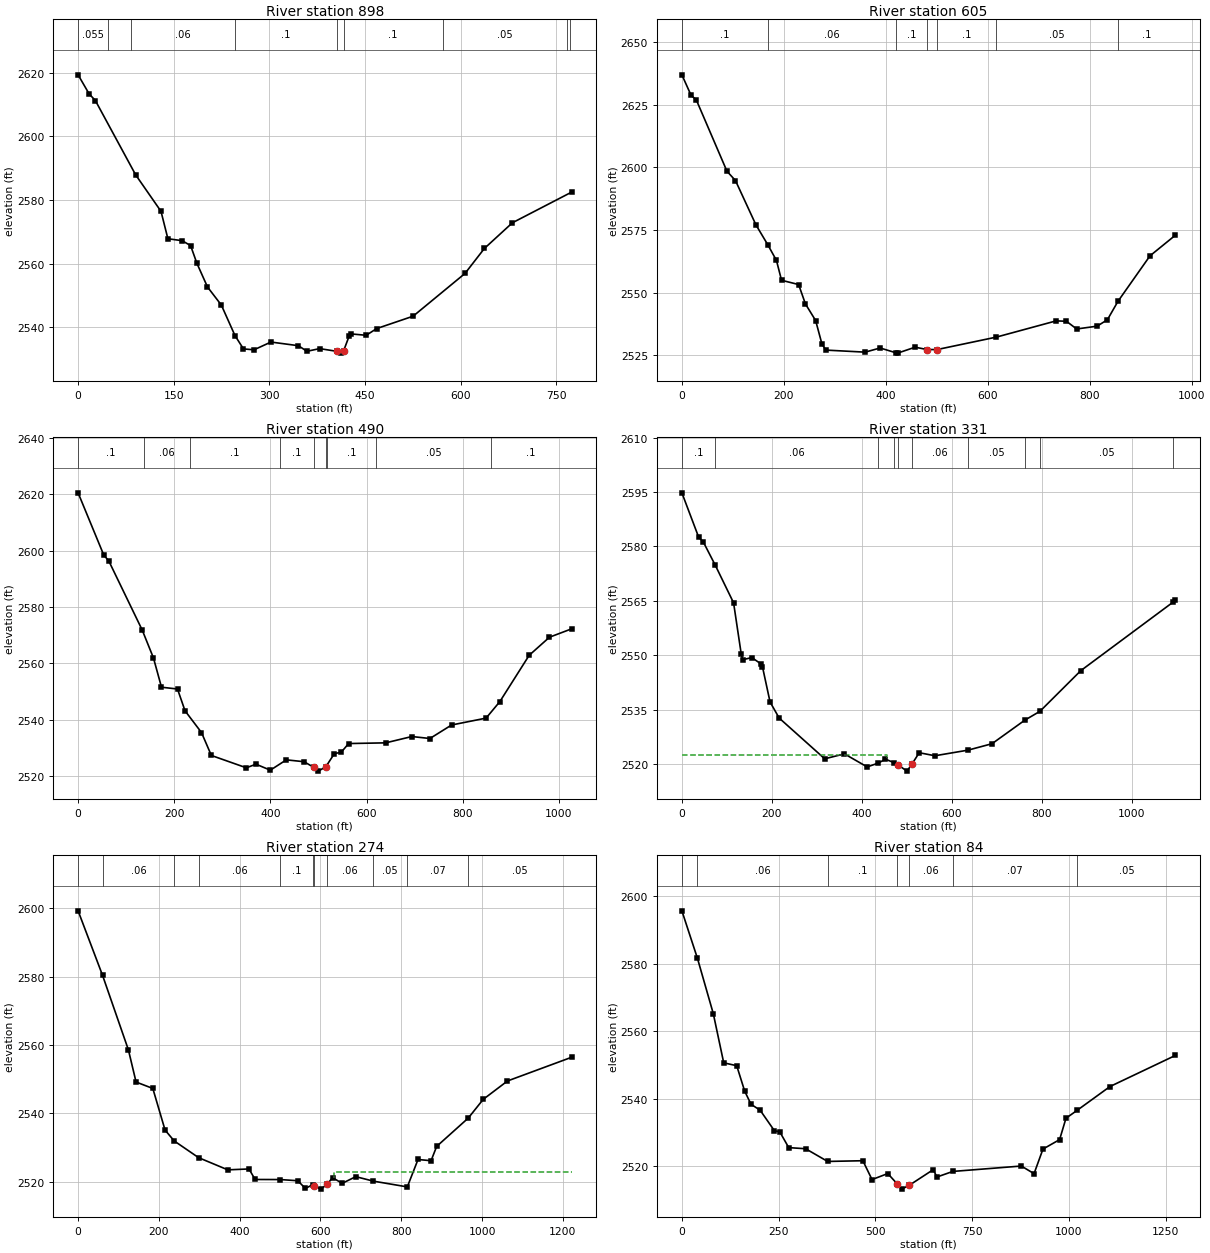
Type RM Length L Ch R = 1 ,898     ,293.2,293.3,294
XS GIS Cut Line= 3
2087527.62712702 421418.321208792088016.70981029421346.035592213
2088287.39726102421276.825756878
#Sta/Elev= 30
       0 2619.29    17.2 2613.34    27.1 2611.21    90.2  2587.9     130 2576.42
   140.8 2567.81   163.1 2567.21   176.4 2565.66   186.3 2560.09   202.9 2552.66
   224.6 2546.99     246  2537.4   259.3 2533.21   275.9 2532.94   302.4 2535.37
   345.5 2534.22   358.8 2532.46   378.7 2533.31   405.2 2532.47   411.9 2531.89
   416.2 2532.55   425.1  2537.3   428.4 2537.92   451.7 2537.49   468.2  2539.6
   525.3 2543.49   606.7 2556.92     637 2564.75     681 2572.83   773.8 2582.45
#Mann= 9 ,-1 , 0
       0    .055       0   46.65      .1       0    82.5     .06       0
  246.12      .1       0   405.2    .045       0   416.2      .1       0
  571.53     .05       0  766.17      .1       0  771.82     .05       0
Bank Sta=405.2,416.2
XS Rating Curve= 0 ,0
Exp/Cntr=0.3,0.1

Type RM Length L Ch R = 1 ,605     ,114.3,114.8,115.1
XS GIS Cut Line= 2
2087533.42182741421732.0486296732088482.54019275421541.227197481
#Sta/Elev= 30
       0 2636.91    18.1 2628.71    28.2 2626.95    88.4 2598.43   105.1 2594.71
   145.3 2577.01   168.6 2569.05   185.5 2562.83   195.5  2554.9     229  2553.2
   242.3 2545.48   262.4 2538.82   274.7 2529.49   282.5 2527.03   359.5 2526.21
   388.9 2527.87   419.7 2525.97   423.1 2525.82   457.6 2528.19   480.9 2527.25
  500.572527.243   616.8 2532.21   734.3  2538.7   754.4 2538.53   774.4 2535.46
   814.6 2536.58   834.7 2539.14   855.5 2546.51   918.3 2564.66   968.1 2572.89
#Mann= 7 ,-1 , 0
       0      .1       0   168.6     .06       0   419.7      .1       0
   480.9    .045       0  500.57      .1       0   616.8     .05       0
   855.5      .1       0
Bank Sta=480.9,500.57
XS Rating Curve= 0 ,0
Exp/Cntr(USF)=0,0
Exp/Cntr=0.3,0.1

Type RM Length L Ch R = 1 ,490     ,161.2,159,157.2
XS GIS Cut Line= 3
2087547.62085345421832.0421661292088076.69164568421739.762495041
2088524.24849334 421541.36098896
#Sta/Elev= 30
       0 2620.51    53.6 2598.36    63.6 2596.44   133.5  2571.8   156.8 2561.93
   173.5 2551.57   206.8 2550.93   222.4 2543.22   256.7 2535.49   277.2 2527.37
     350 2522.99     370 2524.27   399.9 2522.15   433.2 2525.81     470 2525.15
   489.7 2523.21   499.9 2521.81  515.532523.402   533.2 2528.04   547.2 2528.48
   562.8 2531.59   639.9 2531.84   694.3 2534.08   731.9 2533.38   776.9 2538.17
   848.7 2540.61   877.4 2546.48   938.4  2562.9   980.5  2569.3  1026.6 2572.27
#Mann= 9 ,-1 , 0
       0      .1       0   136.2     .06       0  232.82      .1       0
  419.07      .1       0   489.7    .045       0  515.53      .1       0
  518.41      .1       0  620.46     .05       0  858.51      .1       0
Bank Sta=489.7,515.53
XS Rating Curve= 0 ,0
Exp/Cntr=0.3,0.1

Type RM Length L Ch R = 1 ,331     ,58.6,57.8,56
XS GIS Cut Line= 5
2087570.69101727422021.2156722992088012.09597436421915.094165385
2088091.66176012421892.293029875 2088359.6828776421787.440221205
2088531.93843859421576.734933957
#Sta/Elev= 30
       0  2594.8    37.3 2582.56    47.4  2581.3    74.4 2574.78   114.9 2564.45
   131.8  2550.4   135.2 2548.76   155.4 2549.36   175.7 2547.61     179 2546.87
   195.9 2537.12   216.2 2532.67   317.4 2521.43   361.2 2522.79   411.8 2519.19
   436.2 2520.24   452.4 2521.32     471 2520.39   480.6 2519.74   500.1 2518.03
     511 2519.91   527.4 2523.11   562.3 2522.27   635.9 2523.82   689.2 2525.59
     762 2532.08   795.8 2534.54   886.6 2545.76  1091.8 2564.67  1096.7 2565.13
#Mann= 10 ,-1 , 0
       0      .1       0    74.4     .06       0   436.2      .1       0
     471     .06       0   480.6    .045       0     511     .06       0
   635.9     .05       0     762     .07       0   795.8     .05       0
  1091.8      .1       0
#XS Ineff= 2 , 0
           455.6  2522.5     536          2522.5
Permanent Ineff=
       F       F
Bank Sta=480.6,511
XS Rating Curve= 0 ,0
Exp/Cntr=0.5,0.3

Type RM Length L Ch R = 1 ,274     ,187.6,189.3,187.2
XS GIS Cut Line= 5
2087541.46896285422250.3772874622088025.93781018421973.537946135
2088093.60959086421945.8539463732088272.01704243421901.252001464
 2088558.0843837421612.108878955
#Sta/Elev= 30
       0 2599.27    60.6 2580.38   124.6 2558.58   143.5 2549.19     185 2547.31
   215.3 2535.13   237.9 2531.96   298.4 2527.06   370.6  2523.5   423.1 2523.76
   438.2 2520.68   500.5 2520.66     544 2520.31   562.6 2518.06   580.8 2519.16
  584.932518.745   600.9 2517.86  616.432519.261   629.9 2521.22   653.7 2519.55
   687.5 2521.51   730.4 2520.21     815 2518.51   841.5 2526.53   873.8 2526.17
   887.7 2530.36   965.9 2538.65    1003 2544.13    1063  2549.5  1221.7 2556.43
#Mann= 11 ,-1 , 0
       0      .1       0    60.6     .06       0   237.9      .1       0
   298.4     .06       0   500.5      .1       0   580.8     .06       0
  584.93    .045       0  616.43     .06       0   730.4     .05       0
     815     .07       0   965.9     .05       0
#XS Ineff= 2 , 0
                          632.88         2522.78
Permanent Ineff=
       F       F
Bank Sta=584.93,616.43
XS Rating Curve= 0 ,0
Exp/Cntr=0.5,0.3

Type RM Length L Ch R = 1 ,84      ,73.94,84.3,93.96
XS GIS Cut Line= 5
2087550.69696277422265.7571779642088061.31175518422151.945397705
2088130.52159053422125.7994526332088245.87109736422051.975781381
 2088573.4642742421621.336878881
#Sta/Elev= 30
       0  2595.6    40.3  2581.5    81.2 2565.14   108.1 2550.59   141.7 2549.74
   162.2 2542.23   178.6 2538.32   202.2 2536.56   239.1 2530.48   252.9 2530.16
   276.1 2525.48   319.8 2525.15   376.6 2521.39   467.7  2521.6   491.3 2516.02
     532  2517.8   556.5 2514.73   568.1 2513.19   588.1 2514.37   649.4 2518.95
   659.1 2516.78     700 2518.43   877.1 2520.03     910 2517.77     933 2525.05
     976 2527.85   992.5 2534.18  1021.9 2536.57  1106.2 2543.57  1275.2 2552.78
#Mann= 7 ,-1 , 0
       0      .1       0    40.3     .06       0   376.6      .1       0
   556.5    .045       0   588.1     .06       0     700     .07       0
  1021.9     .05       0
Bank Sta=556.5,588.1
XS Rating Curve= 0 ,0
Exp/Cntr=0.5,0.3
LCMann Table=0

Chan Stop Cuts=-1
Use User Specified Reach Order=0
Composite Channel Slope=5